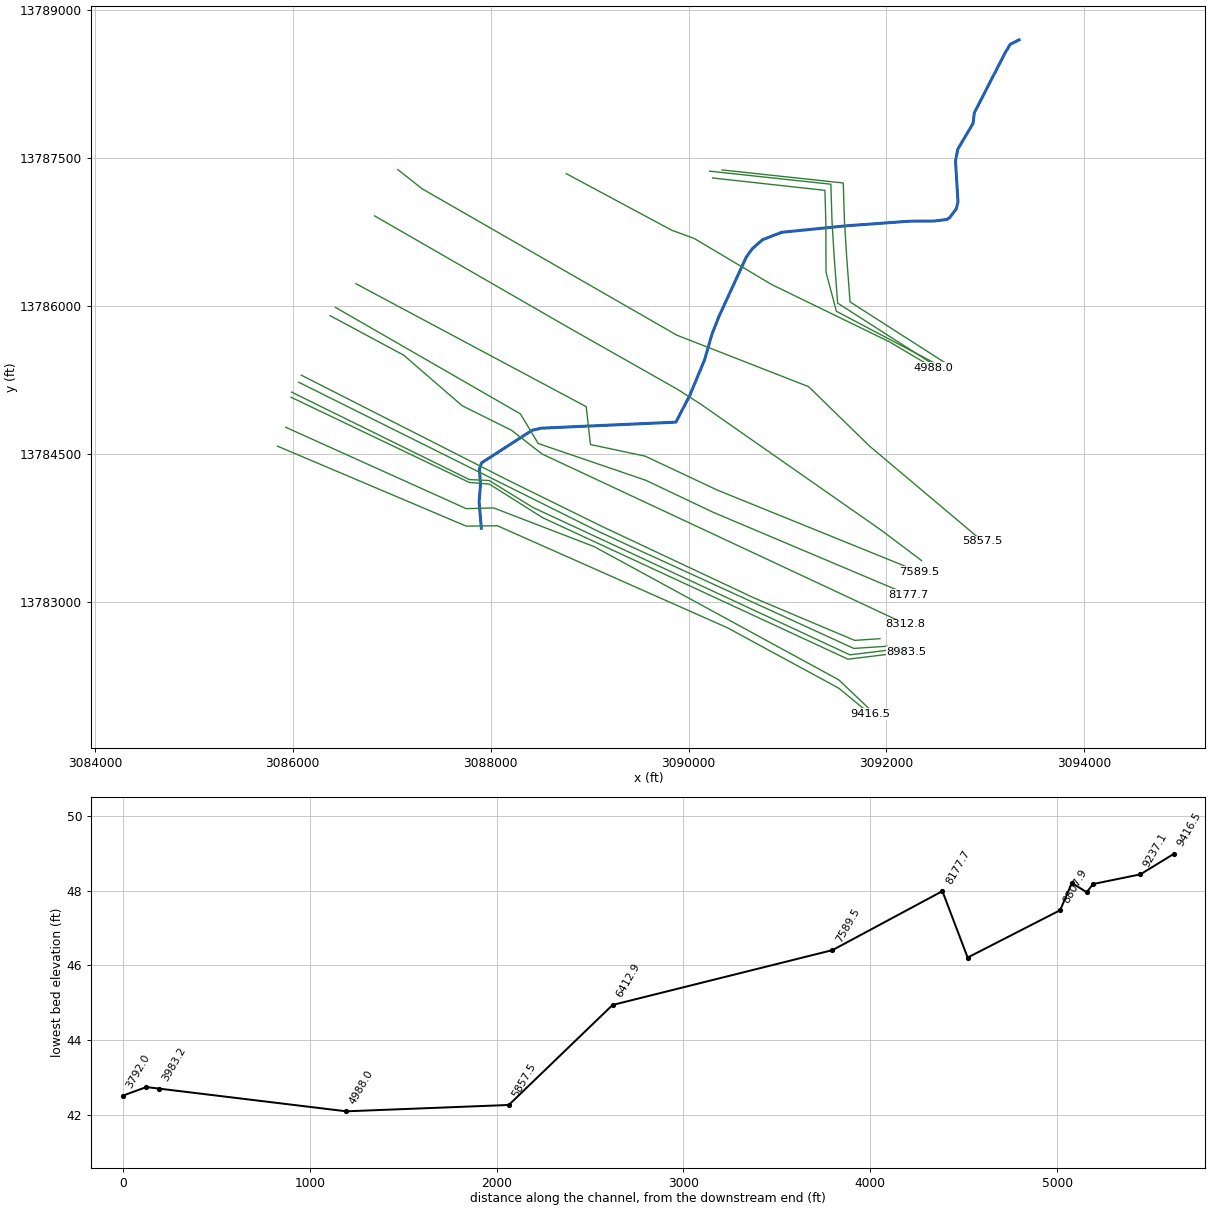
--- C147-00-00.PRJ (project) ---

Proj Title=C147-00-00
Current Plan=p02
Default Exp/Contr=0.3,0.1
English Units
Geom File=g01
Flow File=f03
Flow File=f01
Flow File=f02
Plan File=p01
Plan File=p02
Plan File=p03
Y Axis Title=Elevation
X Axis Title(PF)=Main Channel Distance
X Axis Title(XS)=Station
BEGIN DESCRIPTION:
Sims Bayou Watershed
Tributary 20.25 to Sims Bayou
HCFCD Unit C147-00-00
Flood Hazard Model
10, 2, 1, 0.2% Event
Filename C147-00-00.prj
Prepared by:  Watershed Concepts  Date:
Reviewed by:                      Date:
STATUS FINAL
END DESCRIPTION:
DSS Export Rating Curves= 0
DSS Export Rating Curve Sorted= 0
DSS Export Volume Flow Curves= 0
DXF OffsetX= 0
DXF OffsetY= 0
DXF ScaleX= 1
DXF ScaleY= 10

--- C147-00-00.p02 (plan) ---

Plan Title=Effective Floodway 2015
Program Version=4.1.0
Short Identifier=Eff+LOMR FW
Geom File=g01
Flow File=f02
Subcritical Flow
K Sum by GR= 0
Std Step Tol= 0.01
Critical Tol= 0.01
Num of Std Step Trials= 20
Max Error Tol= 0.3
Flow Tol Ratio= 0.001
Split Flow NTrial= 30
Split Flow Tol= 0.02
Split Flow Ratio= 0.02
Log Output Level= 0
Friction Slope Method= 1
Unsteady Friction Slope Method= 2
Unsteady Bridges Friction Slope Method= 1
Parabolic Critical Depth
Global Vel Dist= 0 , 0 , 0
Global Log Level= 0
CheckData=True
Encroach Param=-1 ,0,0, 2
Encroach River=C147-00-00
Encroach Reach=C147-00-00_0007
Encroach Node=9416.5
       1    4928    5087
Encroach Node=9237.1
       1    4913    5103
Encroach Node=8983.5
       1    4905    5073
Encroach Node=8950.2
       1    4907    5072
Encroach Node=8870.6
       1    4910    5074
Encroach Node=8807.9
       1    4908    5075
Encroach Node=8312.8
       1    4880    5090
Encroach Node=8177.7
       1    4830    5160
Encroach Node=7589.5
       1    4880    5600
Encroach Node=6412.9
       1    4372    5072
Encroach Node=5857.5
       1    4600    5100
Encroach Node=4988.0
       1    4880    5098
Encroach Node=3983.2
       1    4585    5225
Encroach Node=3918.0
       1    4565    5250
Encroach Node=3792.0
       1    4545    5250
Encroach Node=3348.4
       1    4355    5420
Encroach Node=2750.9
       1    3980    5450
Encroach Node=2519.0
       1    3970    5467
Encroach Node=2487.1
       1    4000    5480
Encroach Node=2372.9
       1    4100    5480
Encroach Node=2118.0
       1    4300  5341.1
Encroach Node=1752.9
       1    4650    5275
Encroach Node=1659.0
       1    4650    5250
Encroach Node=1602.4
       1    4650    5250
Encroach Node=1391.0
       1    4650    5600
Encroach Node=982.0
       1    4700    6100
Encroach Node=945.5
       1    4768    6100
Encroach Node=903.5
       1    4768    6100
Encroach Node=746.1
       1    4942    6020
Computation Interval=1HOUR
Output Interval=1HOUR
Run HTab= 0
Run UNet= 0
Run PostProcess= 0
Run WQNet= 0
UNET Theta= 1
UNET Theta Warmup= 1
UNET ZTol= 0.02
UNET ZSATol= 0.1
UNET MxIter= 20
UNET MaxInSteps= 20
UNET DtIC= 0
UNET DtMin= 0
UNET MaxCRTS= 20
UNET WFStab= 2
UNET SFStab= 1
UNET WFX= 1
UNET SFX= 1
UNET DSS MLevel= 4
UNET DZMax Abort= 100
UNET Convert EG Bridges=-1
UNET Use Existing IB Tables=-1
UNET Froude Reduction=False
UNET Froude Limit= 1
UNET Froude Power= 10
UNET Time Slicing=0,0, 5
UNET Junction Losses=0
Instantaneous Interval=1HOUR
Write IC File= 0
Write IC File at Sim End=0
Echo Input=False
Echo Parameters=False
Echo Output=False
Write Detailed= 0
WQ AD Non Conservative
WQ ULTIMATE=-1
WQ Max Comp Step=1HOUR
WQ Output Interval=15MIN
WQ Output Selected Increments= 0
WQ Output face flow=0
WQ Output face velocity=0
WQ Output face area=0
WQ Output face dispersion=0
WQ Output cell volume=0
WQ Output cell surface area=0
WQ Output cell continuity=0
WQ Output cumulative cell continuity=0
WQ Output face conc=0
WQ Output face dconc_dx=0
WQ Output face courant=0
WQ Output face peclet=0
WQ Output face adv mass=0
WQ Output face disp mass=0
WQ Output cell mass=0
WQ Output cell source sink temp=0
WQ Output cell source sink nsm=0
WQ Output MaxMinRange=-1
WQ Daily Max Min Mean=-1
WQ Daily Range=0
WQ Daily Time=0
WQ Create Restart=0
WQ Fixed Restart=0
WQ System Summary=0
WQ Use Fixed Temperature=0
Sorting and Armoring Iterations= 10
XS Update Threshold= 0.02
Hydraulics Update Threshold= 0.02
Energy Slope Method= 1
Volume Change Method= 0
XS Weighting Method= 0
Number of US Weighted Cross Sections= 1
Number of DS Weighted Cross Sections= 1
Upstream XS Weight=0.25
Main XS Weight=0.5
Downstream XS Weight=0.25
Number of DS XS's Weighted with US Boundary= 1
Upstream Boundary Weight= 1
Weight of XSs Associated with US Boundary= 0
Number of US XS's Weighted with DS Boundary= 1
Downstream Boundary Weight= 0.5
Weight of XSs Associated with DS Boundary= 0.5
Sediment Output Level= 4
Mass or Volume Output= 0
Output Increment Type= 1
Profile and TS Output Increment= 10
XS Output Flag= 0
XS Output Increment= 10
Disregard all LS=0
Disregard all Conn=0
Disregard all Breaches=0
Disregard all Pumps=0

--- C147-00-00.p01 (plan) ---

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Plan Title=Effective Multi-Profile 2015
Short Identifier=Eff+LOMR MP
Geom File=g01
Flow File=f01
Encroach Param=-1 ,0,0, 0

--- C147-00-00.p03 (plan) ---

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Plan Title=2015 SV-SQ
Short Identifier=SVSQ+2015
Geom File=g01
Flow File=f03
Encroach Param=-1 ,0,0, 0

--- C147-00-00.f02 (steady flow) ---

Flow Title=Effective Floodway 2015
Program Version=4.10
Number of Profiles= 2
Profile Names=1PCT_100yr,Floodway
River Rch & RM=C147-00-00,C147-00-00_0007 ,9416.5
    4095    4095
River Rch & RM=C147-00-00,C147-00-00_0007 ,6412.9
    4255    4255
River Rch & RM=C147-00-00,C147-00-00_0007 ,5857.5
    4375    4375
River Rch & RM=C147-00-00,C147-00-00_0007 ,4988.0
    4575    4575
River Rch & RM=C147-00-00,C147-00-00_0007 ,3983.2
    4854    4854
River Rch & RM=C147-00-00,C147-00-00_0007 ,2487.1
    4566    4566
River Rch & RM=C147-00-00,C147-00-00_0007 ,746.1
    4510    4510
Boundary for River Rch & Prof#=C147-00-00,C147-00-00_0007 , 1
Up Type= 0
Dn Type= 3
Dn Slope=0.0005
Boundary for River Rch & Prof#=C147-00-00,C147-00-00_0007 , 2
Up Type= 0
Dn Type= 1
Dn Known WS=55.82
DSS Import GetInterval= 0
DSS Import GetPeak= 0
DSS Import FillOption= 0

--- C147-00-00.f01 (steady flow) ---

Flow Title=Effective Multi-Profile 2015
Program Version=4.1.0
Number of Profiles= 6
Profile Names=10PCT_10yr, 4PCT_25yr, 2PCT_50yr, 1PCT_100yr, 1PCT_Plus, 0.2PCT_500yr
River Rch & RM=C147-00-00,C147-00-00_0007 ,9416.5
    2390    2965    3490    4095    4914    5730
River Rch & RM=C147-00-00,C147-00-00_0007 ,6412.9
    2505    3099    3640    4255    5106    5950
River Rch & RM=C147-00-00,C147-00-00_0007 ,5857.5
    2600    3208    3760    4375    5250    6130
River Rch & RM=C147-00-00,C147-00-00_0007 ,4988.0
    2730    3359    3930    4575    5490    6380
River Rch & RM=C147-00-00,C147-00-00_0007 ,3983.2
    2894    3558    4161    4854    5825    6699
River Rch & RM=C147-00-00,C147-00-00_0007 ,2487.1
    2059    2898    3752    4566    5480    6524
River Rch & RM=C147-00-00,C147-00-00_0007 ,746.1
    1993    2825    3677    4510    5412    6456
Boundary for River Rch & Prof#=C147-00-00,C147-00-00_0007 , 1
Up Type= 0
Dn Type= 3
Dn Slope=0.0005
Boundary for River Rch & Prof#=C147-00-00,C147-00-00_0007 , 2
Up Type= 0
Dn Type= 3
Dn Slope=0.0005
Boundary for River Rch & Prof#=C147-00-00,C147-00-00_0007 , 3
Up Type= 0
Dn Type= 3
Dn Slope=0.0005
Boundary for River Rch & Prof#=C147-00-00,C147-00-00_0007 , 4
Up Type= 0
Dn Type= 3
Dn Slope=0.0005
DSS Import GetInterval= 0
DSS Import GetPeak= 0
DSS Import FillOption= 0

--- C147-00-00.f03 (steady flow) ---

Flow Title=SVSQ-2015
Program Version=4.1.0
Number of Profiles= 8
Profile Names=20%_1PCT,40%_1PCT,60%_1PCT,80%_1PCT,100%_1PCT,120%_1PCT,150%_1PCT,220%_1PCT
River Rch & RM=C147-00-00,C147-00-00_0007 ,9416.5
     543  1085.9  1628.9  2171.8  2714.8  3257.7  4072.2  5972.5
River Rch & RM=C147-00-00,C147-00-00_0007 ,3983.2
   960.3  1920.6  2880.8  3841.1  4801.4  5761.7  7202.1 10563.1
River Rch & RM=C147-00-00,C147-00-00_0007 ,2487.1
     890    1780  2670.1  3560.1  4450.1  5340.1  6675.2  9790.2
River Rch & RM=C147-00-00,C147-00-00_0007 ,746.1
   868.9  1737.9  2606.8  3475.8  4344.7  5213.7  6517.1  9558.4
Boundary for River Rch & Prof#=C147-00-00,C147-00-00_0007 , 1
Up Type= 0
Dn Type= 3
Dn Slope=0.0005
Boundary for River Rch & Prof#=C147-00-00,C147-00-00_0007 , 2
Up Type= 0
Dn Type= 3
Dn Slope=0.0005
Boundary for River Rch & Prof#=C147-00-00,C147-00-00_0007 , 3
Up Type= 0
Dn Type= 3
Dn Slope=0.0005
Boundary for River Rch & Prof#=C147-00-00,C147-00-00_0007 , 4
Up Type= 0
Dn Type= 3
Dn Slope=0.0005
DSS Import GetInterval= 0
DSS Import GetPeak= 0
DSS Import FillOption= 0

--- C147-00-00.g01 (geometry) ---

Geom Title=C147-00-00 June 2015
Program Version=4.1.0

River Reach=C147-00-00      ,C147-00-00_0007
Reach XY= 30
 3087905.2909053  13783751.144613087883.1981017113784019.7808837
3087897.0868534713784186.44754513087886.6702076313784349.6417726
 3087907.503499313784412.14197563088419.6563463813784742.5238608
3088513.4064869713784763.35715253089872.6898576313784824.3399701
 3090012.450076813785095.3400843 3090161.680093313785453.1100381
 3090236.300022813785713.30013453090305.1699638113785889.3201236
 3090583.250116313786494.0000166 3090643.249996313786578.9998466
3090748.2501143813786670.99999073090941.7500554613786745.9998407
 3091589.500072313786811.00003883092231.7501001413786857.9999448
3092483.2499252313786859.9999408 3092612.499994813786875.9999088
 3092641.499936813786896.99986683092705.5001368813786982.0000249
3092723.5001008813787051.99988493092698.2501513813787470.0000331
3092722.7501023913787589.00012323092875.7501244713787847.9999333
3092888.2500994713787955.00004743093199.3298578913788560.8899117
3093251.4898585513788648.14006533093341.40995431 13788694.059921

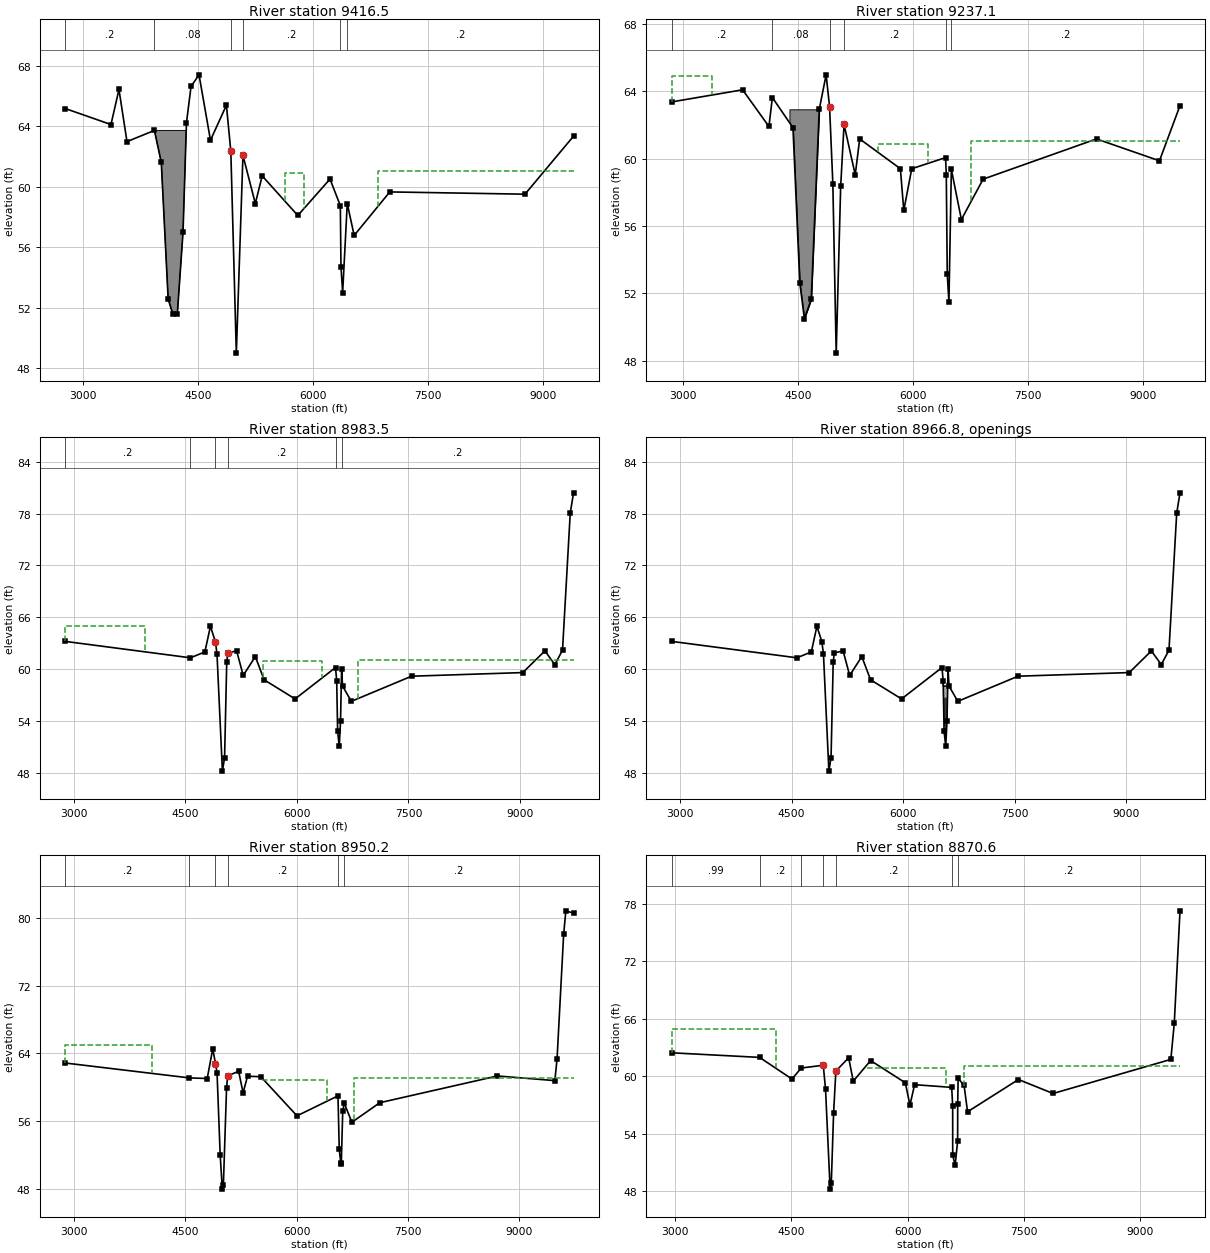
Type RM Length L Ch R = 1 ,9416.5  ,177.7,179.43,192.44
BEGIN DESCRIPTION:
New cross-section due to channel alignment following C147-02-00 instead of C147-00-00
Cross Section 8407.0 channel data used from Effective model
END DESCRIPTION:
XS GIS Cut Line= 6
3085846.2628711313784581.00548313087752.5129956313783771.9779016
3088068.4851327213783775.45000763090393.8899307313782742.6298947
3091518.8499511313782131.53006713091834.1101473913781871.1001417
#Sta/Elev= 30
 2771.18   65.18  3367.1   64.12 3471.39   66.44 3575.67   62.99 3933.23   63.73
 4022.61   61.61    4112   52.58 4171.59   51.59 4231.19   51.56 4305.67   56.99
 4350.37   64.23 4409.96   66.64 4514.25   67.41 4663.23   63.08 4870.73    65.4
 4928.18   62.35    5000   48.99 5086.18   62.08 5247.31   58.89 5336.62   60.72
 5800.67    58.1 6220.04   60.51 6354.58   58.75 6362.88   54.71 6384.78      53
 6444.69   58.89 6534.54   56.78  6998.8   59.66 8759.62   59.51 9391.83   63.35
#Mann= 6 ,-1 , 0
 2771.18      .2       0 3933.23     .08       0 4928.18     .04       0
 5086.18      .2       0 6354.58     .04       0 6444.69      .2       0
#XS Ineff= 3 ,-1
 2771.18    2850   64.94    5635    5880   60.89    6840 9391.83   61.05
Permanent Ineff=
       T       F       T
#Block Obstruct= 1 ,-1
    3933    4348   63.73
Bank Sta=4928.18,5086.18
XS Rating Curve= 0 ,0
Exp/Cntr=0.3,0.1

Type RM Length L Ch R = 1 ,9237.1  ,264.05,253.55,51.18
BEGIN DESCRIPTION:
New cross-section due to channel alignment following C147-02-00 instead of C147-00-00
Cross Section 8201.3 channel data used from Effective model
END DESCRIPTION:
XS GIS Cut Line= 6
3085929.5963658813784771.97787023087752.5129956313783949.0612089
 3088030.290655313783956.00542073089047.20102306 13783564.105614
3091518.1898474713782216.16014713091841.8899874713781908.4501326
#Sta/Elev= 30
  2853.7   63.37  3779.1   64.09 4122.39   61.91 4167.17   63.63 4435.83   61.84
 4525.39   52.61 4585.09   50.49 4674.65   51.64 4779.13   62.93 4868.38   64.98
 4913.44   63.09 4956.13   58.51    5000   48.44  5058.5   58.37 5102.37   62.03
 5248.16   59.04 5306.43   61.17 5837.02    59.4 5881.56   56.92  5985.5    59.4
 6426.86   60.06 6436.03   59.05 6448.63   53.16 6470.53   51.45 6502.03   59.36
 6632.95   56.38  6916.8   58.78 8395.81   61.17 9216.85   59.87 9484.82   63.15
#Mann= 6 ,-1 , 0
  2853.7      .2       0 4167.17     .08       0 4913.44     .04       0
 5102.37      .2       0 6426.86     .04       0 6502.03      .2       0
#XS Ineff= 3 ,-1
  2853.7    3380   64.94    5540    6200   60.89    6760 9484.82   61.05
Permanent Ineff=
       T       T       T
#Block Obstruct= 1 ,-1
    4390    4780   62.93
Bank Sta=4913.44,5102.37
XS Rating Curve= 0 ,0
Exp/Cntr=0.5,0.3

Type RM Length L Ch R = 1 ,8983.5  ,28.8,33.28,48.14
BEGIN DESCRIPTION:
New cross-section due to channel alignment following C147-02-00 instead of C147-00-00
Cross Section 8148.8 channel data used from Effective model
END DESCRIPTION:
XS GIS Cut Line= 6
 3085983.019159313785076.26663163087783.8006627313784214.2877126
3087986.9255845513784197.36058113088524.6859919713783857.5167726
3091612.1699744813782425.14004413092199.86007205  13782497.21011
#Sta/Elev= 30
 2887.07    63.2 4570.65    61.3 4764.33   61.98 4838.83   64.95 4905.57   63.17
  4927.2   61.75    5000   48.18 5029.12   49.73 5058.23   60.81 5072.79   61.85
 5190.91   62.11 5279.68   59.26 5442.41   61.44 5560.76   58.75 5976.93   56.54
 6520.07   60.17 6536.07   58.66 6548.67   52.77 6570.57   51.06 6587.37   53.94
 6602.07   59.97 6614.82   58.03 6732.82   56.26 7542.55   59.17 9037.61   59.59
 9334.54    62.1 9467.76   60.51 9571.38   62.19    9675   78.04  9719.4    80.4
#Mann= 6 ,-1 , 0
 2887.07      .2       0 4570.65     .08       0 4905.57     .04       0
 5072.79      .2       0 6520.07     .04       0 6602.07      .2       0
#XS Ineff= 3 ,-1
 2887.07    3960   64.94    5550    6340   60.89    6820  9719.4   61.05
Permanent Ineff=
       T       T       T
Bank Sta=4905.57,5072.79
XS Rating Curve= 0 ,0
Exp/Cntr=0.5,0.3

Type RM Length L Ch R = 4 ,8966.8  ,,,
Bridge Culvert--1,0,-1,-1, 0
Deck Dist Width WeirC Skew NumUp NumDn MinLoCord MaxHiCord MaxSubmerge Is_Ogee
2,28,3,0, 21, 21, , , 0.98, 0, 1,1,,
 6536.07 6538.37 6540.37 6547.27 6548.67 6558.37 6559.47 6561.57 6570.57 6576.27
 6578.17 6578.57 6578.67 6587.37 6594.86 6594.97 6595.08 6595.26 6595.37 6595.47
 6602.07
   58.59   58.04   58.03   58.03   58.03   58.02   58.02   58.02   58.02   58.01
   58.01   58.01   58.01      58      58      58      58      58      58      58
    59.9
   58.58   57.59   56.73   56.73   56.73   56.72   56.72   56.72   56.72   56.71
   56.71   56.71   56.71    56.7   56.93   56.98   57.02    57.1   57.14   57.18
   59.89
 6563.12 6565.42 6567.42 6574.32 6575.72 6585.42 6586.52 6588.62 6597.62 6603.32
 6605.22 6605.62 6605.72 6614.42 6621.91 6622.02 6622.13 6622.31 6622.42 6622.52
 6629.12
   58.59   58.04   58.03   58.03   58.03   58.02   58.02   58.02   58.02   58.01
   58.01   58.01   58.01      58      58      58      58      58      58      58
   57.47
   58.59    57.6   56.74   56.74   56.74   56.73   56.73   56.73   56.73   56.72
   56.72   56.72   56.72   56.71   56.94   56.99
        
Pier Skew, UpSta & Num, DnSta & Num=  ,6547.27, 2 ,6574.32, 2 , 0 , 0 , 0 ,,
       1       1
   52.46   57.73
       1       1
   52.47   57.74
Pier Skew, UpSta & Num, DnSta & Num=  ,6561.57, 2 ,6588.62, 2 , 0 , 0 , 0 ,,
       1       1
    50.3   57.72
       1       1
   50.31   57.73
Pier Skew, UpSta & Num, DnSta & Num=  ,6576.27, 2 ,6603.32, 2 , 0 , 0 , 0 ,,
       1       1
   50.05   57.71
       1       1
   50.06   57.72
Pier Skew, UpSta & Num, DnSta & Num=  ,6587.37, 2 ,6614.42, 2 , 0 , 0 , 0 ,,
       1       1
   52.74   57.72
       1       1
   52.75   57.73
BR Coef=-1 , 1 , 0 ,1.25, 0 ,,,0.8,0,2,0,
WSPro=,,,, 1 ,,,, 0 ,,,, 0 ,,,,-1 ,-1 ,-1 , 0 , 0 , 0 , 0 , 0
BC Mult= 1 ,2887.07,6450,2882.86,6460
BC Mult= 3 ,6450,9719.4,6460,9732.69
BC Design=,, 0 ,, 0 ,,,,,,
BC Use User HTab Curves=0
BC User HTab FreeFlow(D)= 0

Type RM Length L Ch R = 1 ,8950.2  ,120.13,79.65,70.71
BEGIN DESCRIPTION:
New cross-section due to channel alignment following C147-02-00 instead of C147-00-00
Cross Section 8100.8 channel data used from Effective model
END DESCRIPTION:
XS GIS Cut Line= 6
3085988.2274822113785128.35018893087785.1024973813784242.9333246
3087984.3212590513784233.81884153088429.8482551413783959.4017394
3091631.5698700513782469.03989073092219.2599676413782541.1099566
#Sta/Elev= 30
 2882.86   62.86 4557.16    61.1 4796.34   61.03 4871.09   64.54 4907.93    62.8
 4928.77   61.72 4971.51   51.94    5000   47.96 5014.24   48.46 5056.98   59.85
 5071.22   61.34 5220.02   61.88 5279.82   59.34 5339.62    61.3 5519.02   61.24
 6006.47   56.62 6558.61   58.98 6575.72   52.66 6597.62   50.95 6603.32   51.03
 6622.52   57.15 6642.08   58.14 6745.83   55.86 7122.13   58.17 8707.06   61.33
 9481.05   60.78 9510.65   63.35 9599.47   78.05 9629.07   80.84 9732.69   80.56
#Mann= 6 ,-1 , 0
 2882.86      .2       0 4557.16     .08       0 4907.93     .04       0
 5071.22      .2       0 6558.61     .04       0 6642.08      .2       0
#XS Ineff= 3 ,-1
 2882.86    4050   64.94    5530    6405   60.89    6780 9732.69   61.05
Permanent Ineff=
       T       T       T
Bank Sta=4907.93,5071.22
XS Rating Curve= 0 ,0
Exp/Cntr=0.5,0.3

Type RM Length L Ch R = 1 ,8870.6  ,65.05,62.66,66.35
BEGIN DESCRIPTION:
New cross-section due to channel alignment following C147-02-00 instead of C147-00-00
Cross Section 8039.5 channel data used from Effective model
END DESCRIPTION:
XS GIS Cut Line= 6
3086059.7033891413785228.29290243089067.7485541413783728.6636838
3089302.14014572 13783619.4401493089390.0799304713783578.4700866
3091670.4598841413782534.08995753092009.7699010513782556.3500836
#Sta/Elev= 30
 2953.44   62.45 4088.76   61.97 4507.03   59.71 4626.54   60.86 4910.92   61.15
 4940.24   58.69    5000   48.21 5014.94   48.86 5044.81   56.18 5073.87   60.54
 5239.01   61.93 5298.76   59.49 5522.84   61.64 5970.98   59.32 6030.74   56.98
 6090.49   59.12 6569.73   58.84 6582.53   56.89 6582.93   51.73 6614.73   50.73
 6646.53   53.22 6647.43   57.09 6652.83   59.78 6729.89   59.04 6774.68   56.29
 7431.58   59.66 7879.46    58.2  9400.1   61.76 9444.45   65.53 9518.37   77.28
#Mann= 7 ,-1 , 0
 2953.44     .99       0 4088.76      .2       0 4626.54     .08       0
 4910.92     .04       0 5073.87      .2       0 6569.73     .04       0
 6652.83      .2       0
#XS Ineff= 3 ,-1
 2953.44    4300   64.94    5480    6500   60.89    6730 9518.37   61.05
Permanent Ineff=
       T       T       T
Bank Sta=4910.92,5073.87
XS Rating Curve= 0 ,0
Exp/Cntr=0.5,0.3

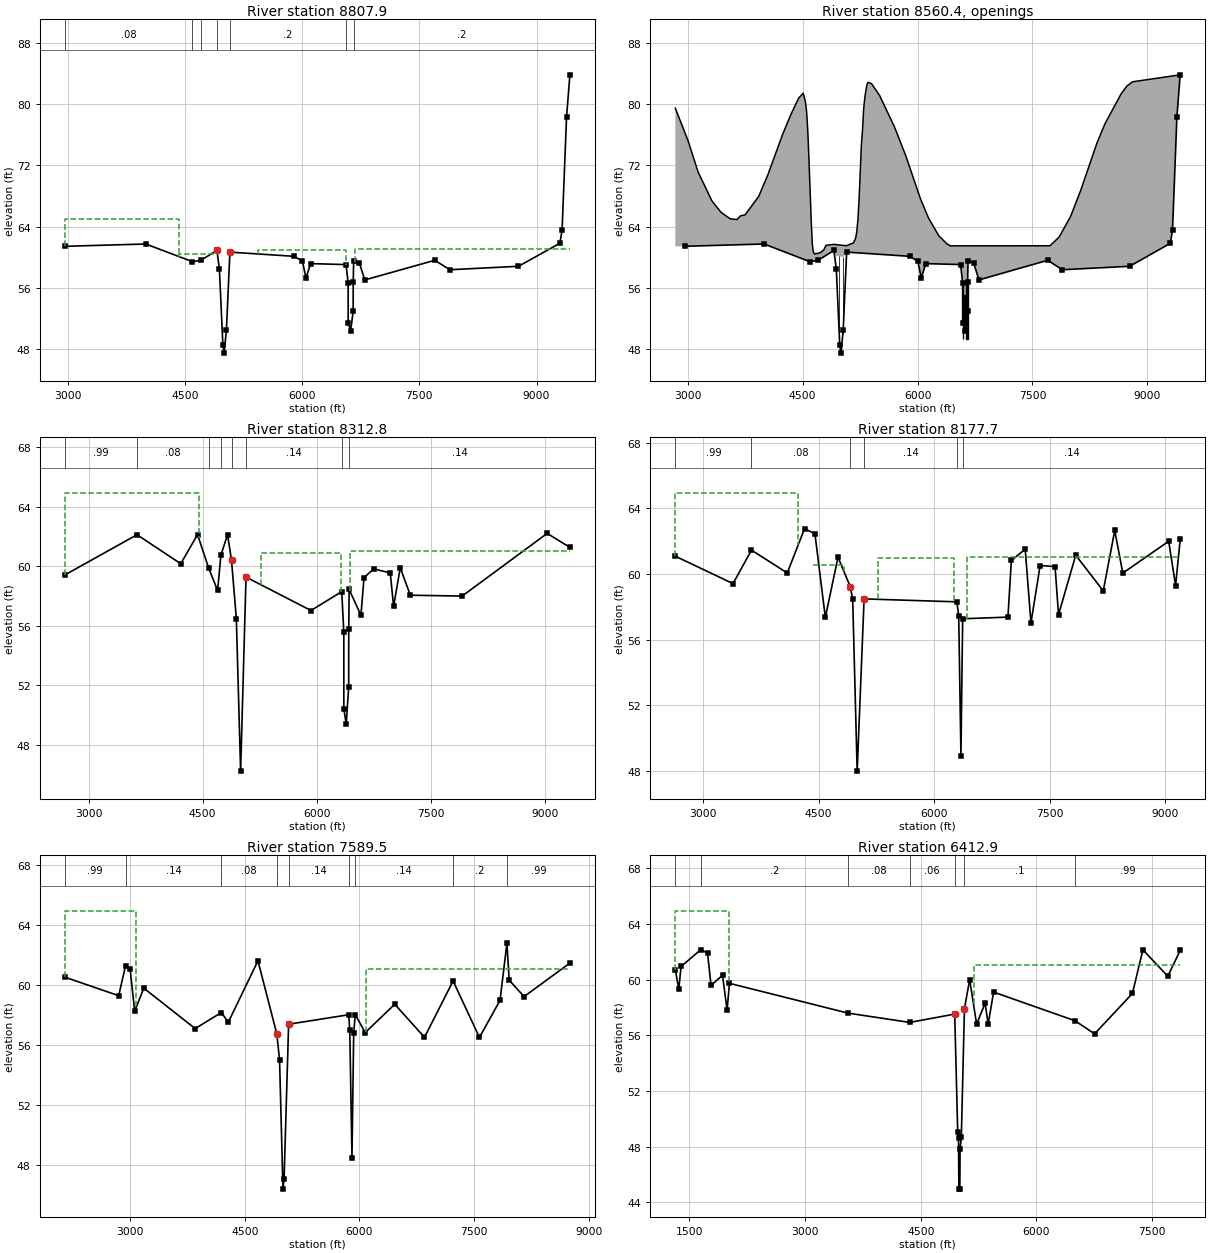
Type RM Length L Ch R = 1 ,8807.9  ,528.51,495.07,373.91
BEGIN DESCRIPTION:
New cross-section due to channel alignment following C147-02-00 instead of C147-00-00
Cross Section 7958.3 channel data used from Effective model
END DESCRIPTION:
XS GIS Cut Line= 6
3086085.7453318113785299.9075886 3088166.9084923 13784240.879851
3089127.0401022113783768.01006183090665.08000514 13783043.649962
3091678.8440537213782615.4096767 3091934.920641313782632.7705344
#Sta/Elev= 30
 2964.26   61.43  3997.1   61.73 4595.85   59.42 4700.63   59.59  4908.8   60.89
 4940.13   58.47 4985.03   48.51    5000   47.48 5029.94   50.44 5074.85   60.67
 5898.69   60.12 6003.56   59.48 6048.51   57.29 6108.44   59.17  6561.8   59.04
 6588.73   56.59 6589.13   51.43 6620.93   50.43 6652.73   52.92 6653.63   56.79
 6658.93   59.48 6732.94   59.23 6801.64   57.04 7697.46    59.6 7890.74   58.37
 8768.89   58.82 9298.76   61.82 9327.27   63.54 9384.31    78.3 9427.09   83.82
#Mann= 7 ,-1 , 0
 2964.26     .08       0 4595.85    .015       0 4700.63     .08       0
  4908.8     .04       0 5074.85      .2       0  6561.8     .04       0
 6658.93      .2       0
#XS Ineff= 4 ,-1
 2964.26    4425   64.94    4425    4871   60.42    5440    6560      61
    6670 9427.09   61.05
Permanent Ineff=
       T       T       T       T
Bank Sta=4908.8,5074.85
XS Rating Curve= 0 ,0
Exp/Cntr=0.5,0.3

Type RM Length L Ch R = 4 ,8560.4  ,,,
BEGIN DESCRIPTION:
Beltway 8 Mainlanes & Feeders
END DESCRIPTION:
Bridge Culvert--1,0,-1,-1, 0
Deck Dist Width WeirC Skew NumUp NumDn MinLoCord MaxHiCord MaxSubmerge Is_Ogee
209,76,2.6,0, 60, 60, , , 0.98, 0, 0,0,,
 2839.45 3003.38 3137.51 3316.34 3435.56 3554.79  3644.2 3688.91 3748.52 3927.36
 4046.58 4240.32 4344.64 4448.96 4508.57 4538.38 4553.28 4568.18 4583.08 4612.89
 4627.79  4642.7  4657.6 4732.11 4776.82 4806.63 4910.57 5074.55 5089.46 5163.27
 5192.95 5207.79 5222.64 5237.48 5267.16    5282 5296.85 5311.69 5326.53 5341.37
 5356.22 5400.74 5504.64 5697.59 5846.01 6038.96 6142.86 6277.14 6381.85 6426.72
 7728.11 7847.78 7997.37 8131.99 8341.41 8446.12 8655.54 8730.33 8805.12 9427.09
   79.46   75.27   71.11   67.37   65.87   65.02   64.92   65.41   65.52   67.95
   70.75   76.07   78.58   80.79   81.42   80.23   78.92   76.44   72.82   64.75
   61.62   60.62   60.42    60.6   60.96   61.56   61.68    61.5   61.58   61.87
    62.5   63.38   65.01   67.63   74.66    76.6   79.34   80.81   81.79   82.62
   82.85   82.65   81.13   77.05   73.27   67.61   65.13   62.81   61.77   61.49
    61.5   62.64   65.33   68.81   74.92   77.44   81.32   82.34   82.91   83.82
                                                                                
                                                                                
                                                   60.18      60
                                                                                
                                                                                
                                                                                
 2691.24 2839.45 3003.38 3137.51 3256.73 3271.63 3361.05 3554.79  3644.2 3688.91
 3748.52 3927.36 4046.58 4240.32 4344.64 4448.96 4508.57 4538.38 4553.28 4568.18
 4583.08 4612.89 4627.79  4642.7 4764.46 4852.79 4867.51 5103.05  5103.9 5118.74
 5163.27 5192.95 5207.79 5222.64 5237.48 5267.16    5282 5296.85 5311.69 5326.53
 5341.37 5356.22 5400.74 5504.64 5697.59 5846.01 6038.96 6142.86 6277.14 6381.85
 6426.72 7728.11 7847.78 7997.37 8131.99 8341.41 8446.12 8655.54 8790.17  9329.2
      80   79.46   75.27   71.11   68.48   68.43   66.65   65.02   64.92   65.41
   65.52   67.95   70.75   76.07   78.58   80.79   81.42   80.23   78.92   76.44
   72.82   64.75   61.62   60.62   60.52   60.83   61.05   60.89   61.07   61.79
   61.87    62.5   63.38   65.01   67.63   74.66    76.6   79.34   80.81   81.79
   82.62   82.85   82.65   81.13   77.05   73.27   67.61   65.13   62.81   61.77
   61.49    61.5   62.64   65.33   68.81   74.92   77.44   81.32   82.87   83.82
                                                                                
                                                                                
                                                   59.55   59.39
                                                                                
                                                                                
                                                                                
Pier Skew, UpSta & Num, DnSta & Num=  ,4975.5, 2 ,4973.5, 2 , 0 , 0 , 0 ,,
       2       2
      40      62
       2       2
      40      62
Pier Skew, UpSta & Num, DnSta & Num=  ,5025.5, 2 ,5025.5, 2 , 0 , 0 , 0 ,,
       2       2
      40      62
       2       2
      40      62
Abutment Skew #Up #Dn= , 3 , 3
 4887.04    4918  4929.4
   59.63   59.63   57.96
 4887.04    4918  4929.4
   59.63   59.63   57.96
BR Coef=-1 , 0 , 0 ,, 0 ,,,1.23,0,,0,
WSPro=,,,, 1 ,,,, 0 ,,,, 0 ,,,,-1 ,-1 ,-1 , 0 , 0 , 0 , 0 , 0
Culvert=2,7,10,353.6,0.015,0.4,1,8,1,49.33,6593.4,49.32,6362.4,Culvert #1  , 0 ,10
Culvert Bottom n=0.015
Culvert=2,4,8,353.6,0.015,0.4,1,8,1,51.04,6604.3,49.93,6373.3,Culvert #2  , 0 ,10
Culvert Bottom n=0.015
Culvert=2,4,8,353.6,0.015,0.4,1,8,1,51.04,6613.3,49.93,6382.3,Culvert #3  , 0 ,10
Culvert Bottom n=0.015
Culvert=2,4,8,353.6,0.015,0.4,1,8,1,51.04,6624.2,49.93,6393.2,Culvert #4  , 0 ,10
Culvert Bottom n=0.015
Culvert=2,7,10,353.6,0.015,0.4,1,8,1,49.33,6635.8,49.92,6404.8,Culvert #5  , 0 ,10
Culvert Bottom n=0.015
Culvert=2,7,10,353.6,0.015,0.4,1,8,1,49.33,6647.9,49.92,6416.9,Culvert #6  , 0 ,10
Culvert Bottom n=0.015
BC Mult= 1 ,2964.26,4000,2691.24,4000
BC Mult= 3 ,4000,5800,4000,5800
BC Mult= 2 ,5750,6950,5750,6950
BC Mult= 1 ,6950,9427.09,6950,9329.2
BC Design=,, 0 ,, 0 ,,,,,,
BC Use User HTab Curves=0
BC User HTab FreeFlow(D)= 0

Type RM Length L Ch R = 1 ,8312.8  ,166.78,135.11,236.13
BEGIN DESCRIPTION:
Downstream Section of Bridge/Culvert/Weir
New cross-section due to channel alignment following C147-02-00 instead of C147-00-00
Cross Section 7584.7 channel data used from Effective model
END DESCRIPTION:
XS GIS Cut Line= 6
  3086378.49704213785901.5786293 3087120.684534913785502.2729975
 3087712.185976613784990.4377351 3088210.449743813784742.1737959
 3088520.641052613784501.2963249 3092195.337115213782780.3401212
#Sta/Elev= 30
 2691.24   59.42 3637.34   62.12 4212.92   60.17 4433.43   62.13 4579.93   59.87
 4697.13   58.37 4741.08   60.76 4828.97   62.12 4880.27   60.39 4943.52   56.48
    5000   46.21 5070.91   59.27 5924.34   57.02 6329.75   58.29 6356.67   55.55
 6357.07   50.39 6388.87   49.39 6420.67   51.88 6421.57   55.75 6426.87   58.44
 6581.87    56.7 6622.47   59.23 6748.57   59.82 6967.64   59.55 7011.46   57.29
 7099.09    59.9 7230.82   58.05 7912.55   57.99 9030.96   62.21  9329.2   61.27
#Mann= 8 ,-1 , 0
 2691.24     .99       0 3637.34     .08       0 4579.93    .015       0
 4741.08     .08       0 4880.27     .04       0 5070.91     .14       0
 6329.75     .04       0 6426.87     .14       0
#XS Ineff= 4 ,-1
 2691.24    4450   64.94    4515    4785   60.54    5270    6320   60.89
    6439  9329.2   61.05
Permanent Ineff=
       T       T       T       T
Bank Sta=4880.27,5070.91
XS Rating Curve= 0 ,0
Exp/Cntr=0.5,0.3

Type RM Length L Ch R = 1 ,8177.7  ,632.49,588.23,227.81
BEGIN DESCRIPTION:
New cross-section due to channel alignment following C147-02-00 instead of C147-00-00
Cross Section 7366.9 channel data used from Effective model
END DESCRIPTION:
XS GIS Cut Line= 6
   3086431.4483813785985.7799045 3088301.239916613784907.6547641
 3088480.710358113784607.9604816 3089567.840073613784235.9599133
 3090247.699934413783912.4398911 3092225.719272313783075.4789666
#Sta/Elev= 30
 2637.88   61.08 3387.31   59.41 3627.12   61.45 4091.77   60.06  4316.6   62.76
 4451.49   62.44 4586.39   57.35 4751.26   61.02 4910.97   59.21 4941.78   58.45
    5000   47.99 5090.06   58.48 6294.89    58.3 6319.13   57.42 6347.83   48.94
 6370.33   57.27  6958.3   57.37 7003.09   60.83 7182.83    61.5 7257.47   57.02
 7376.75   60.51 7570.57   60.45  7615.3   57.51 7838.95   61.14 8196.78   58.97
 8345.87   62.65 8450.24   60.05 9046.63   61.99 9136.09   59.29 9195.73    62.1
#Mann= 6 ,-1 , 0
 2637.88     .99       0 3627.12     .08       0 4910.97     .04       0
 5090.06     .14       0 6294.89     .04       0 6370.33     .14       0
#XS Ineff= 4 ,-1
 2637.88    4235   64.94    4425    4827   60.54    5270    6258      61
    6425 9195.73   61.05
Permanent Ineff=
       T       T       T       T
Bank Sta=4910.97,5090.06
XS Rating Curve= 0 ,0
Exp/Cntr=0.3,0.1

Type RM Length L Ch R = 1 ,7589.5  ,915.24,1176.74,791.4
BEGIN DESCRIPTION:
New cross-section due to channel alignment following C147-02-00 instead of C147-00-00
Cross Section 7152.0 channel data used from Effective model
END DESCRIPTION:
XS GIS Cut Line= 6
  3086638.04573613786225.3634148 3088966.170673313784980.5716131
 3089008.310024713784597.6101086 3089561.7498627 13784480.210081
 3090291.290070313784136.4099156 3092328.907714213783309.5359131
#Sta/Elev= 30
 2152.54   60.52 2853.56   59.29 2943.05   61.28 3002.71   61.08 3062.37   58.26
  3181.7   59.79 3852.89    57.1 4195.94   58.17 4285.43   57.52 4673.23   61.61
 4919.46   56.75 4955.55   55.02    5000   46.41 5014.82    47.1 5074.09   57.39
 5858.59   58.02 5873.12   56.98 5901.82    48.5 5924.32   56.83 5944.85   58.03
 6074.24   56.83 6460.79   58.72  6849.3   56.52 7223.28   60.27 7567.34   56.51
  7836.6   58.98 7926.36   62.78 7956.28   60.32 8150.75   59.23 8749.12   61.46
#Mann= 9 ,-1 , 0
 2152.54     .99       0 2943.05     .14       0 4195.94     .08       0
 4919.46     .04       0 5074.09     .14       0 5858.59     .04       0
 5944.85     .14       0 7223.28      .2       0 7926.36     .99       0
#XS Ineff= 2 ,-1
 2152.54    3085   64.94    6080 8749.12   61.05
Permanent Ineff=
       T       T
Bank Sta=4919.46,5074.09
XS Rating Curve= 0 ,0
Exp/Cntr=0.3,0.1

Type RM Length L Ch R = 1 ,6412.9  ,478.4,555.4,699.9
BEGIN DESCRIPTION:
Cross Section 6412.9-INTERPOLATED - extended ROB & LOB
END DESCRIPTION:
XS GIS Cut Line= 6
  3086826.41346913786912.2846131 3088791.480077813785779.3000025
 3089891.949989713785154.3901631 3090117.920010213785010.3399262
 3091946.709987813783731.3198465 3092355.927345213783422.7013692
#Sta/Elev= 30
 1317.31   60.71 1362.08    59.3 1391.92   60.94 1645.62   62.14 1735.15   61.91
 1779.92   59.58 1929.15   60.31 1988.84    57.8 2018.69   59.73 3555.75   57.59
    4357   56.92  4939.9   57.52  4978.9   49.03  4989.8   48.64  4993.5   44.94
  5006.2   44.95  5009.5   47.81  5025.9    48.7  5065.9    57.9  5133.9      60
  5223.9    56.8  5333.9    58.3  5373.9    56.8  5443.9    59.1    6500   57.04
  6753.9    56.1  7243.9      59 7380.05   62.14 7702.22   60.24 7863.31   62.09
#Mann= 7 ,-1 , 0
 1317.31     .99       0 1645.62      .2       0 3555.75     .08       0
    4357     .06       0  4939.9     .04       0  5065.9      .1       0
    6500     .99       0
#XS Ineff= 2 ,-1
 1317.31 2018.69   64.94  5183.9 7863.31   61.05
Permanent Ineff=
       T       F
Bank Sta=4939.9,5065.9
XS Rating Curve= 0 ,0
Exp/Cntr=0.3,0.1

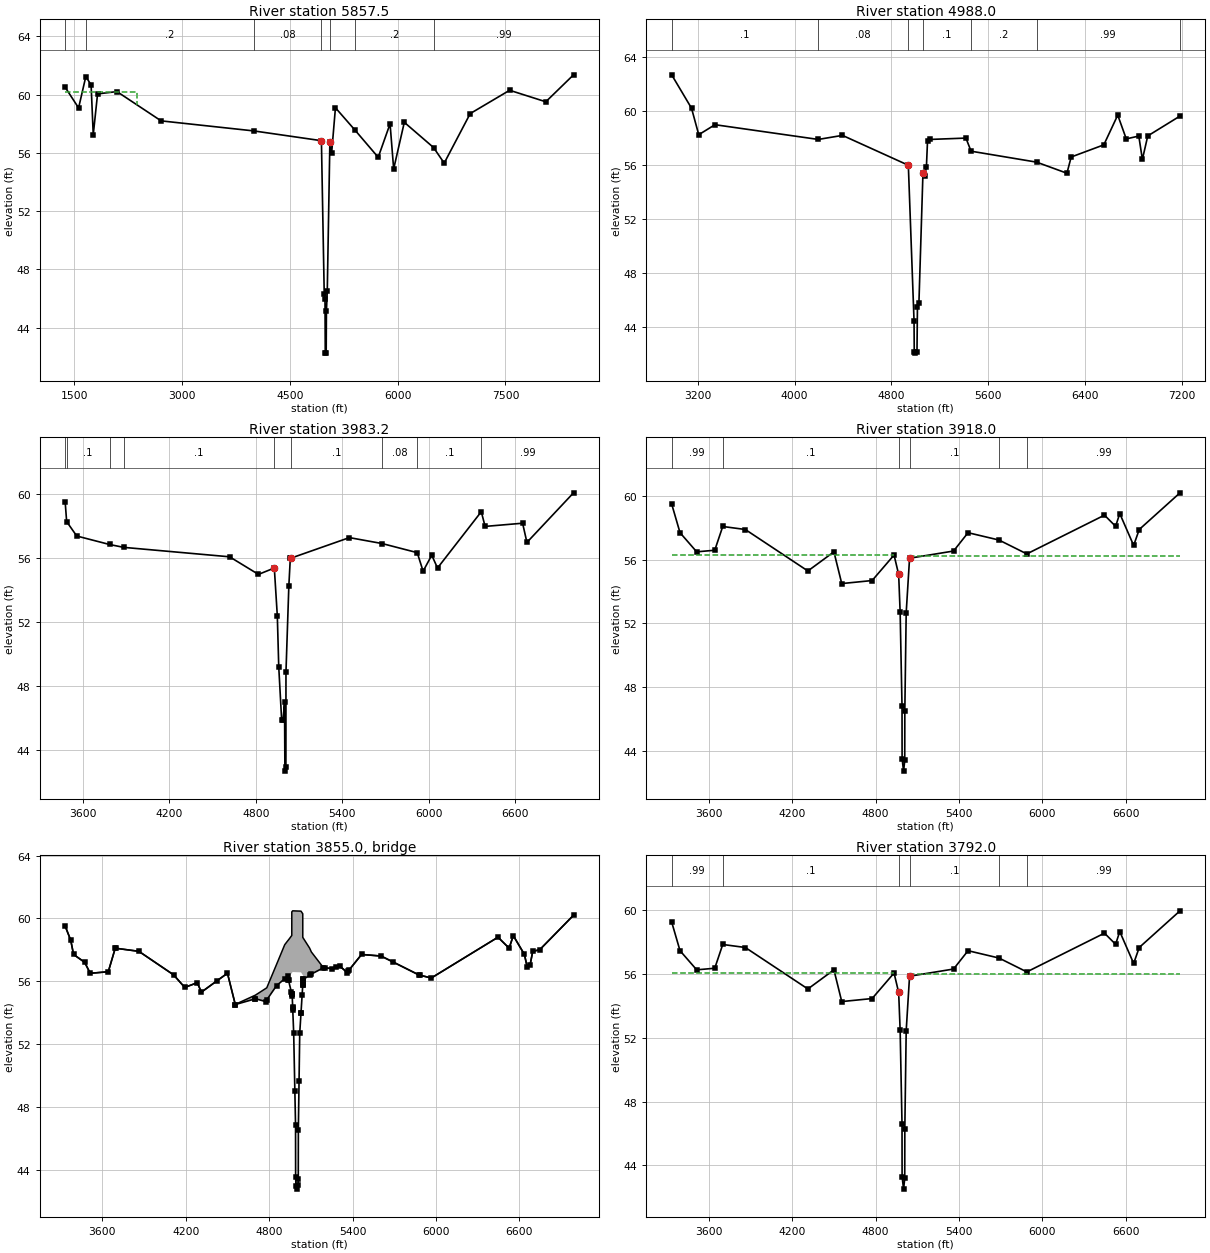
Type RM Length L Ch R = 1 ,5857.5  ,965.2,869.5,821
BEGIN DESCRIPTION:
Cross Section 5857.5 - extended ROB & LOB
END DESCRIPTION:
XS GIS Cut Line= 6
  3087060.78865713787381.0346599  3087308.18448813787185.7220584
 3089881.519892513785704.8798757 3091214.010009613785183.2700266
 3091830.470062813784581.0399318 3092972.246978713783618.0136426
#Sta/Elev= 30
 1375.49    60.5 1561.75   59.09 1662.04   61.24 1735.65   60.67 1765.63   57.25
 1825.58   60.05 2095.35   60.21 2709.82    58.2    4000   57.51  4939.9   56.84
  4978.9   46.35  4989.8   45.96  4993.5   42.26  5006.2   42.27  5009.5   45.13
  5021.5   46.55  5057.7   56.77  5082.1      56    5135    59.1  5411.4   57.54
    5730    55.7    5895      58    5945    54.9  6093.1    58.1    6500   56.37
  6648.1    55.3  7009.9    58.7  7558.5    60.3 8061.62   59.51 8447.43   61.36
#Mann= 7 ,-1 , 0
 1375.49     .99       0 1662.04      .2       0    4000     .08       0
  4939.9     .04       0  5057.7     .08       0  5411.4      .2       0
    6500     .99       0
#XS Ineff= 2 , 0
       0  2380.1   60.19    5135       0    59.1
Permanent Ineff=
       T       F
Bank Sta=4939.9,5057.7
XS Rating Curve= 0 ,0
Exp/Cntr=0.3,0.1

Type RM Length L Ch R = 1 ,4988.0  ,1340.9,1004.8,475.7
BEGIN DESCRIPTION:
Cross Section 4988.0 - extended ROB & LOB
END DESCRIPTION:
XS GIS Cut Line= 6
  3088764.00047413787339.5472101 3089828.4100906 13786767.559837
 3090056.030042113786684.1000301 3090839.950062213786217.3401369
 3092026.670129713785639.4200329 3092472.796534113785375.5659018
#Sta/Elev= 30
 2983.05   62.68 3147.15   60.21 3206.82   58.25 3341.08   58.99    4195    57.9
    4395    58.2  4939.6   55.99  4986.7   44.48  4988.5   42.18  4996.6   42.09
  5011.1   42.19  5014.9   45.53  5027.1    45.8  5060.6   55.45  5073.5   55.19
    5089   55.85  5098.3    57.8  5119.3    57.9  5415.8      58  5458.2   57.03
    6000   56.22  6250.8    55.4  6285.8    56.6  6555.8    57.5  6670.8    59.7
 6741.25   57.94 6844.91   58.15 6874.53   56.42 6918.95   58.16 7185.52   59.63
#Mann= 7 ,-1 , 0
 2983.05      .1       0    4195     .08       0  4939.6     .04       0
  5060.6      .1       0  5458.2      .2       0    6000     .99       0
 7185.52     .99       0
#XS Ineff= 2 , 0
       0    4395    58.2  5415.8       0      58
Permanent Ineff=
       F       F
Bank Sta=4939.6,5060.6
XS Rating Curve= 0 ,0
Exp/Cntr=0.3,0.1

Type RM Length L Ch R = 1 ,3983.2  ,78.2,65.2,65.1
BEGIN DESCRIPTION:
Cross Section 3983.2-Interpolated
END DESCRIPTION:
XS GIS Cut Line= 6
      3090242.58     13787295.71      3091378.28     13787170.34
      3091387.81     13786852.24      3091389.44      13786342.6
      3091494.53     13785946.31       3092506.7     13785412.02
#Sta/Elev= 30
  3477.7    59.5  3487.7    58.3  3557.7    57.4    3785   56.87  3883.5   56.69
  4617.8    56.1  4817.8      55  4927.8    55.4  4948.6    52.4  4958.6    49.2
  4978.6    45.9  4988.6    45.9  4998.6      47  5001.2    42.7  5008.1   42.95
  5008.6    48.9  5028.6    54.3  5038.6      56  5044.2   56.02  5448.2    57.3
  5674.7   56.93  5918.8   56.36  5959.5    55.2  6019.5    56.2  6059.5    55.4
    6363   58.92  6389.5      58  6649.5    58.2  6679.5      57  7002.7    60.1
#Mann= 9 , 1 , 0
  3477.7      .2       0  3487.7      .1       0    3785     .08       0
  3883.5      .1       0  4927.8     .04       0  5044.2      .1       0
  5674.7     .08       0  5918.8      .1       0    6363     .99       0
#XS Ineff= 2 , 0
       0                  5448.2       0    57.3
Permanent Ineff=
       F       F
Bank Sta=4927.8,5044.2
XS Rating Curve= 0 ,0
Exp/Cntr=0.5,0.3

Type RM Length L Ch R = 1 ,3918.0  ,126,126,126
BEGIN DESCRIPTION:
Upstream Section of Bridge/Culvert/Weir
END DESCRIPTION:
XS GIS Cut Line= 6
      3090213.71     13787364.47      3091438.67     13787232.43
      3091450.07     13786856.11      3091472.59     13786489.27
      3091507.06     13786028.92      3092533.79     13785370.55
#Sta/Elev= 30
  3332.6   59.49  3392.6   57.69  3512.6   56.49  3642.6   56.59    3700   58.08
  3862.6   57.89  4312.6   55.29    4500   56.49  4556.2    54.5  4774.8   54.69
  4932.6   56.29  4965.8   55.07  4976.4   52.71  4989.9   46.81  4990.5   43.52
  5001.2   42.74  5009.5   43.41  5010.1   46.53    5020   52.68  5044.2   56.09
  5360.8   56.54    5465   57.69  5687.6   57.23    5888   56.36  6446.6   58.79
  6526.6   58.09  6556.6   58.89  6656.6   56.89  6696.6   57.89    6990   60.19
#Mann= 6 , 1 , 0
  3332.6     .99       0    3700      .1       0  4965.8     .04       0
  5044.2      .1       0  5687.6     .08       0    5888     .99       0
#XS Ineff= 2 , 0
       0  4932.6    56.3    5056       0    56.2
Permanent Ineff=
       F       F
Bank Sta=4965.8,5044.2
XS Rating Curve= 0 ,0
Exp/Cntr=0.5,0.3

Type RM Length L Ch R = 3 ,3855.0  ,,,
BEGIN DESCRIPTION:
SOUTH POST OAK ROAD
Structure ID: C47-4
END DESCRIPTION:
Bridge Culvert--1,0,-1,-1, 0
Deck Dist Width WeirC Skew NumUp NumDn MinLoCord MaxHiCord MaxSubmerge Is_Ogee
10,106,2.6,0, 49, 49, , , 0.95, 0, 1,1,,
  3332.6  3372.6  3392.6  3472.6  3512.6  3642.6  3692.6  3862.6  4112.6  4192.6
  4282.6  4312.6    4500  4556.2  4701.4  4774.8    4783  4853.8  4911.9  4932.6
 4939.11  4939.2 4962.79  4962.9  4969.1  5029.2  5041.9 5042.01 5046.09  5046.2
  5091.5  5103.6  5190.4  5249.9  5307.7  5360.8    5465    5605  5876.6  5966.6
  6446.6  6526.6  6556.6  6636.6  6656.6  6676.6  6696.6  6746.6    6990
    59.5    58.6    57.7    57.2    56.5    56.6    58.1    57.9    56.4    55.6
    55.9    55.3   56.51   54.52   55.11   55.53   55.58   57.08   58.32   58.56
   58.63   58.63   58.91   60.41   60.48   60.46   60.29   58.79   58.73   58.73
    58.1   57.86   56.86   56.81   56.97   56.56    57.7    57.6    56.4    56.2
    58.8    58.1    58.9    57.7    56.9      57    57.9      58    60.2
    59.5    58.6    57.7    57.2    56.5    56.6    58.1    57.9    56.4    55.6
    55.9    55.3    56.5   54.51   54.88    54.7   54.81   55.72   56.15    56.3
   56.06   56.23   56.51   56.51   56.58   56.56   56.39   56.39   56.33   56.11
   56.38   56.45   56.85    56.8   56.96   56.55    57.7    57.6    56.4    56.2
    58.8    58.1    58.9    57.7    56.9      57    57.9      58    60.2
  3332.6  3372.6  3392.6  3472.6  3512.6  3642.6  3692.6  3862.6  4112.6  4192.6
  4282.6  4312.6    4500  4556.2  4701.4  4774.8    4783  4853.8  4911.9  4932.6
 4939.11  4939.2 4962.79  4962.9  4969.1  5029.2  5041.9 5042.01 5046.09  5046.2
  5091.5  5103.6  5190.4  5249.9  5307.7  5360.8    5465    5605  5876.6  5966.6
  6446.6  6526.6  6556.6  6636.6  6656.6  6676.6  6696.6  6746.6    6990
    59.5    58.6    57.7    57.2    56.5    56.6    58.1    57.9    56.4    55.6
    55.9    55.3   56.51   54.52   55.11   55.53   55.58   57.08   58.32   58.56
   58.63   58.63   58.91   60.41   60.48   60.46   60.29   58.79   58.73   58.73
    58.1   57.86   56.86   56.81   56.97   56.56    57.7    57.6    56.4    56.2
    58.8    58.1    58.9    57.7    56.9      57    57.9      58    60.2
   59.27   58.37   57.47   56.97   56.27   56.37   57.87   57.67   56.17   55.37
   55.67   55.07   56.27   54.28   54.65   54.47   54.58   55.49   55.92   56.07
   55.83      56   56.28   56.28   56.35   56.33   56.16   56.16    56.1   55.88
   56.15   56.22   56.62   56.57   56.73   56.32   57.47   57.37   56.17   55.97
   58.57   57.87   58.67   57.47   56.67   56.77   57.67   57.77   59.97
Abutment Skew #Up #Dn= , 2 , 2
    4939  4984.9
   56.23   49.01
    4939  4984.9
      56   48.78
Abutment Skew #Up #Dn= , 2 , 2
  5015.1 5046.29
   49.65   56.33
  5015.1 5046.29
   49.42    56.1
BR Coef= 1 , 1 , 0 ,1.25, 0 ,,,0.8,-1,2,0,
WSPro=,,,, 1 ,,,, 0 ,,,, 0 ,,,,-1 ,-1 ,-1 , 0 , 0 , 0 , 0 , 0
BR U #Sta/Elev= 79
  3332.6    59.5  3372.6    58.6  3392.6    57.7  3472.6    57.2  3512.6    56.5
  3642.6    56.6  3692.6    58.1    3700   58.09  3862.6    57.9  4112.6    56.4
  4192.6    55.6  4282.6    55.9  4312.6    55.3  4421.2      56    4500    56.5
  4556.2   54.51  4556.4   54.51  4695.2   54.86  4701.4   54.88  4774.8    54.7
    4783   54.81  4853.8   55.72  4911.9   56.15  4932.6    56.3 4939.11   56.06
  4939.2   56.06  4958.8   55.34 4962.79   55.19  4962.9   55.19 4963.01   55.18
  4965.8   55.08  4969.1   54.35  4969.2   54.32    4970   54.14  4976.4   52.72
  4984.9   49.01  4989.9   46.82  4990.5   43.53  4992.9   42.95  5001.2   42.75
  5008.1      43  5009.5   43.42  5010.1   46.54  5015.1   49.65    5020   52.69
  5029.1   53.97  5029.2   53.99  5037.1    55.1 5041.79   55.76  5041.9   55.78
 5042.01   55.79  5044.2    56.1 5046.09   56.11  5046.2   56.11  5091.5   56.38
  5103.6   56.45  5190.4   56.85  5201.9   56.84  5249.9    56.8  5281.6   56.89
  5307.7   56.96  5360.8   56.55  5367.9   56.63  5374.4    56.7    5465    57.7
    5605    57.6  5687.6   57.24  5876.6    56.4    5888   56.37  5966.6    56.2
  6446.6    58.8  6526.6    58.1  6556.6    58.9  6636.6    57.7  6656.6    56.9
  6676.6      57  6696.6    57.9  6746.6      58    6990    60.2
BR U #Mann= 6
  3332.6     .99    3700      .1  4965.8     .04  5044.2      .1  5687.6     .08
    5888     .99
BR U Banks=4965.8,5044.2
BR D #Sta/Elev= 79
  3332.6   59.27  3372.6   58.37  3392.6   57.47  3472.6   56.97  3512.6   56.27
  3642.6   56.37  3692.6   57.87    3700   57.86  3862.6   57.67  4112.6   56.17
  4192.6   55.37  4282.6   55.67  4312.6   55.07  4421.2   55.77    4500   56.27
  4556.2   54.28  4556.4   54.28  4695.2   54.63  4701.4   54.65  4774.8   54.47
    4783   54.58  4853.8   55.49  4911.9   55.92  4932.6   56.07 4939.11   55.83
  4939.2   55.83  4958.8   55.11 4962.79   54.96  4962.9   54.96 4963.01   54.95
  4965.8   54.85  4969.1   54.12  4969.2   54.09    4970   53.91  4976.4   52.49
  4984.9   48.78  4989.9   46.59  4990.5    43.3  4992.9   42.72  5001.2   42.52
  5008.1   42.77  5009.5   43.19  5010.1   46.31  5015.1   49.42    5020   52.46
  5029.1   53.74  5029.2   53.76  5037.1   54.87 5041.79   55.53  5041.9   55.55
 5042.01   55.56  5044.2   55.87 5046.09   55.88  5046.2   55.88  5091.5   56.15
  5103.6   56.22  5190.4   56.62  5201.9   56.61  5249.9   56.57  5281.6   56.66
  5307.7   56.73  5360.8   56.32  5367.9    56.4  5374.4   56.47    5465   57.47
    5605   57.37  5687.6   57.01  5876.6   56.17    5888   56.14  5966.6   55.97
  6446.6   58.57  6526.6   57.87  6556.6   58.67  6636.6   57.47  6656.6   56.67
  6676.6   56.77  6696.6   57.67  6746.6   57.77    6990   59.97
BR D #Mann= 6
  3332.6     .99    3700      .1  4965.8     .04  5044.2      .1  5687.6     .08
    5888     .99
BR D Banks=4965.8,5044.2
BC Design=,, 0 ,, 0 ,,,,,,
BC HTab HWMax=60.19
BC Use User HTab Curves=0
BC User HTab FreeFlow(D)= 0

Type RM Length L Ch R = 1 ,3792.0  ,443.6,443.6,443.6
BEGIN DESCRIPTION:
Downstream Section of Bridge/Culvert/Weir
END DESCRIPTION:
XS GIS Cut Line= 6
      3090339.08     13787377.05      3091564.05     13787245.01
      3091575.45     13786868.69      3091597.97     13786501.85
      3091632.44      13786041.5      3092659.16     13785383.13
#Sta/Elev= 30
  3332.6   59.26  3392.6   57.46  3512.6   56.26  3642.6   56.36    3700   57.85
  3862.6   57.66  4312.6   55.06    4500   56.26  4556.2   54.27  4774.8   54.46
  4932.6   56.06  4965.8   54.84  4976.4   52.48  4989.9   46.58  4990.5   43.29
  5001.2   42.51  5009.5   43.18  5010.1    46.3    5020   52.45  5044.2   55.86
  5360.8   56.31    5465   57.46  5687.6      57    5888   56.13  6446.6   58.56
  6526.6   57.86  6556.6   58.66  6656.6   56.66  6696.6   57.66    6990   59.96
#Mann= 6 , 1 , 0
  3332.6     .99       0    3700      .1       0  4965.8     .04       0
  5044.2      .1       0  5687.6     .08       0    5888     .99       0
#XS Ineff= 2 , 0
       0  4932.6   56.07    5056       0      56
Permanent Ineff=
       F       F
Bank Sta=4965.8,5044.2
XS Rating Curve= 0 ,0
Exp/Cntr=0.5,0.3