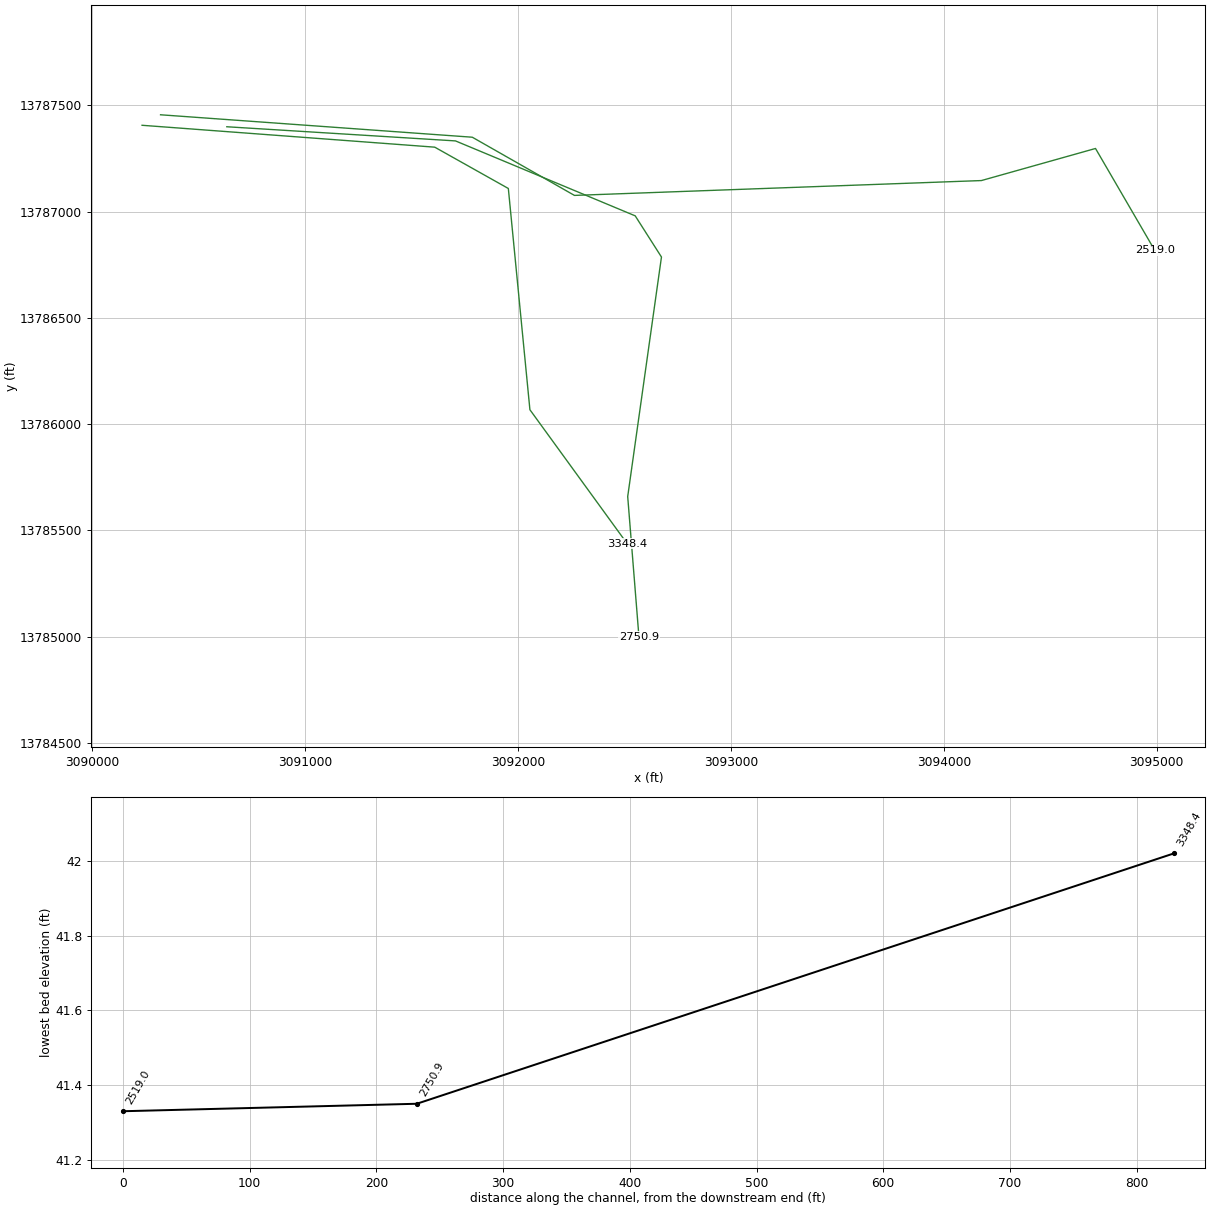
HEC-RAS study C147-00-00.PRJ: C147-00-00

--- C147-00-00.g01 (geometry) --- (continued)

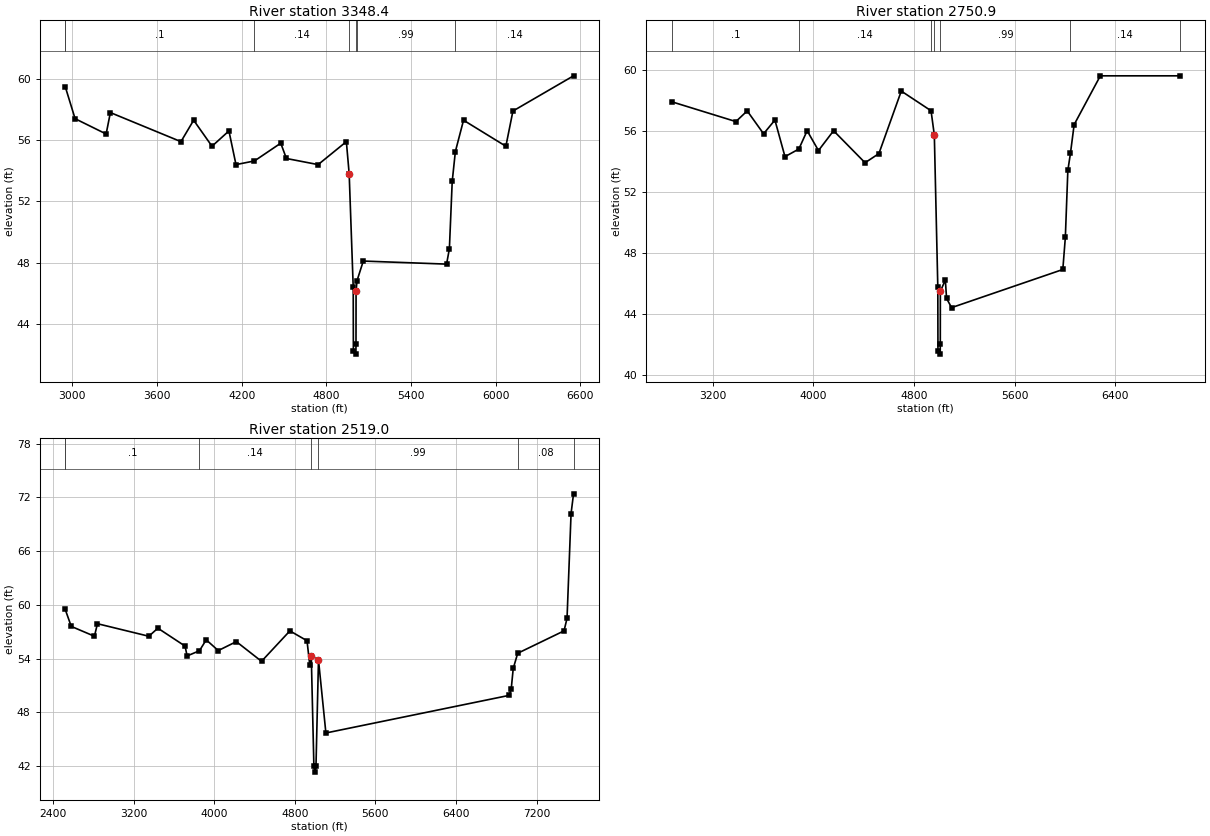
Type RM Length L Ch R = 1 ,3348.4  ,499.4,597.5,623.2
BEGIN DESCRIPTION:
Cross Section 3348.4-INTERPOLATED
END DESCRIPTION:
XS GIS Cut Line= 5
      3090234.66     13787406.42      3091609.31     13787303.42
      3091954.98     13787108.98      3092056.29     13786067.63
      3092513.67      13785436.6
#Sta/Elev= 30
  2949.1    59.5  3019.1    57.4  3239.1    56.4  3269.1    57.8  3769.1    55.9
  3859.1    57.3  3989.1    55.6  4109.1    56.6  4159.1    54.4  4289.9   54.64
  4476.3    55.8  4516.3    54.8  4741.1    54.4  4941.1    55.9  4961.1    53.8
  4989.7    46.4  4990.8   42.24  5008.7   42.02  5009.4   42.68  5009.9   46.13
  5016.7   46.82  5061.1    48.1  5651.1    47.9  5671.1    48.9  5691.1    53.3
  5713.4   55.25  5771.3    57.3  6071.3    55.6  6121.3    57.9  6550.7    60.2
#Mann= 7 , 1 , 0
  2949.1      .2       0  2949.1      .1       0  4289.9     .14       0
  4961.1     .02       0  5009.9     .14       0  5016.7     .99       0
  5713.4     .14       0
#XS Ineff= 2 , 0
       0  3859.1    57.3               0
Permanent Ineff=
       F       F
Bank Sta=4961.1,5009.9
XS Rating Curve= 0 ,0
Exp/Cntr=0.3,0.1

Type RM Length L Ch R = 1 ,2750.9  ,51.4,231.9,1425
BEGIN DESCRIPTION:
Cross Section 2750.9
END DESCRIPTION:
XS GIS Cut Line= 6
      3090632.75     13787399.48      3091706.69     13787332.89
      3092550.82     13786980.19      3092674.13     13786786.41
      3092515.58     13785658.96      3092568.43     13784998.34
#Sta/Elev= 30
  2875.7    57.9  3385.7    56.6  3475.7    57.3  3605.7    55.8  3695.7    56.7
  3775.7    54.3  3885.9    54.8  3951.7      56  4041.7    54.7  4161.7      56
  4411.7    53.9  4521.7    54.5  4699.5    58.6  4935.9   57.31    4962   55.72
  4989.7   45.73  4990.8   41.57  5008.7   41.35  5009.4   42.01  5009.9   45.46
  5049.5   46.22  5059.2      45  5099.2    44.4  5982.6    46.9  6002.6      49
  6022.6    53.4  6043.1   54.51  6072.6    56.4  6280.6    59.6  6913.4    59.6
#Mann= 7 ,-1 , 0
  2875.7      .1       0  3885.9     .14       0  4935.9     .08       0
    4962     .02       0  5009.9     .99       0  6043.1     .14       0
  6913.4      .2       0
Bank Sta=4962,5009.9
XS Rating Curve= 0 ,0
Exp/Cntr=0.3,0.1

Type RM Length L Ch R = 1 ,2519.0  ,20.5,31.9,41.5
BEGIN DESCRIPTION:
Cross Section 2519.0-INTERPOLATED
END DESCRIPTION:
XS GIS Cut Line= 6
      3090321.47     13787455.86      3091785.74     13787350.23
      3092265.47     13787076.37      3094176.86     13787146.26
      3094712.76     13787297.26      3094991.08     13786817.62
#Sta/Elev= 30
  2520.9    59.5  2580.9    57.6  2810.9    56.5  2840.9    57.9  3350.9    56.5
  3440.9    57.4  3710.9    55.4  3730.9    54.3  3853.3   54.88  3920.9    56.1
  4040.4    54.9  4219.8    55.9  4469.8    53.7  4751.4    57.1  4921.4      56
  4948.7    53.3 4963.83   54.26 4989.53   42.06 5001.83   41.33 5010.53   42.03
 5035.33   53.86  5108.8    45.7  6928.6    49.9  6948.6    50.6  6968.6    52.9
    7013    54.6  7472.8    57.1  7502.8    58.5  7542.8    70.2  7567.3    72.4
#Mann= 7 , 1 , 0
  2520.9      .2       0  2520.9      .1       0  3853.3     .14       0
 4963.83     .04       0 5035.33     .99       0    7013     .08       0
  7567.3      .2       0
Bank Sta=4963.83,5035.33
XS Rating Curve= 0 ,0
Exp/Cntr=0.5,0.3