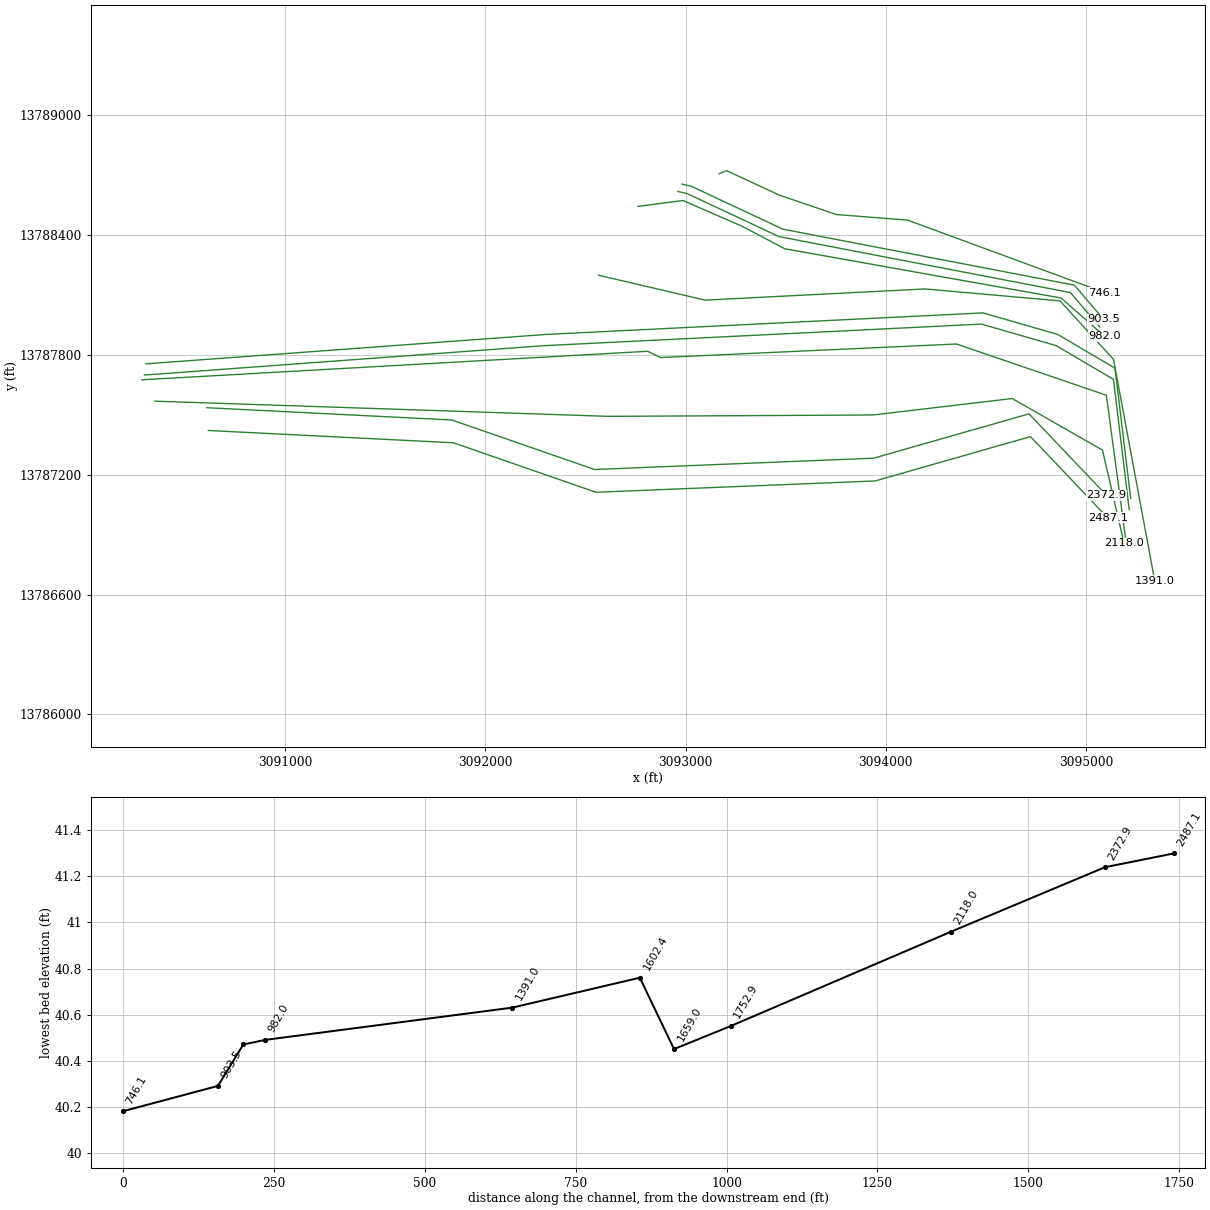
HEC-RAS study C147-00-00.PRJ: C147-00-00

--- C147-00-00.g01 (geometry) --- (continued)

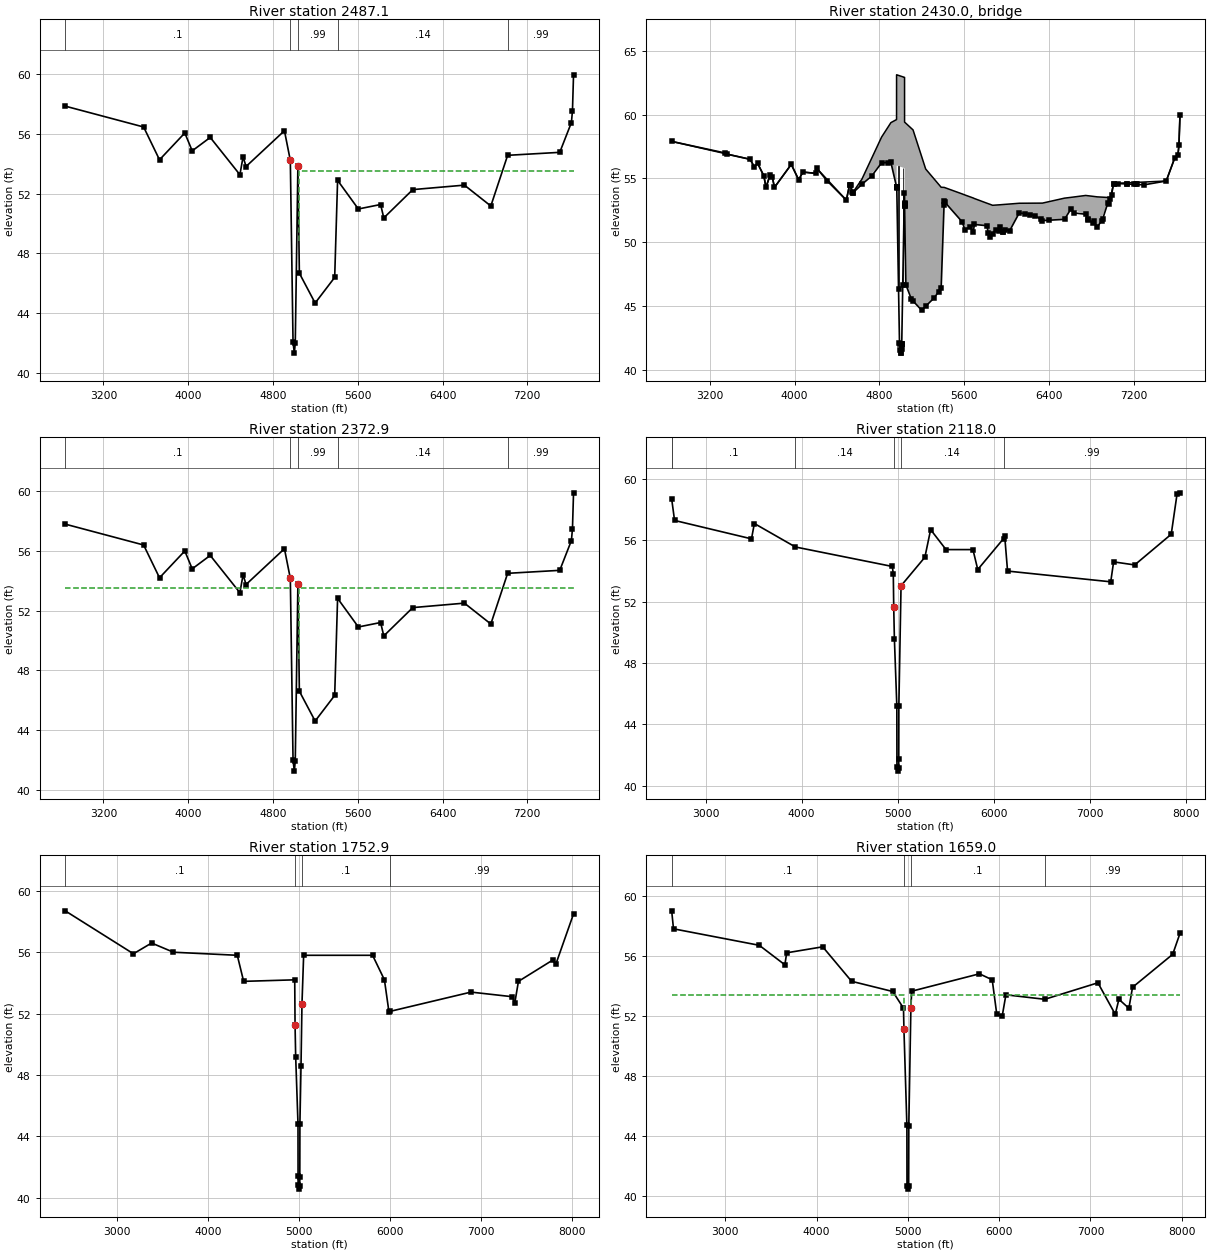
Type RM Length L Ch R = 1 ,2487.1  ,114.2,114.2,114.2
BEGIN DESCRIPTION:
Upstream Section of Bridge/Culvert/Weir
END DESCRIPTION:
XS GIS Cut Line= 6
      3090615.95     13787421.02      3091840.11     13787359.53
      3092552.59      13787111.8      3093946.97     13787168.48
      3094722.67     13787390.37      3095108.47      13786983.7
#Sta/Elev= 30
  2839.5   57.87  3579.5   56.47  3729.5   54.27    3968   56.07    4038   54.87
    4208   55.77    4488   53.27  4517.9   54.47  4546.1   53.82  4908.3   56.22
  4963.8   54.23  4989.5   42.03  5001.8    41.3  5010.5      42  5035.3   53.83
  5049.2   46.66    5198   44.66  5382.5   46.38  5409.9   52.89  5605.8   50.97
  5815.8   51.27  5845.8   50.37  6119.4   52.27  6606.6   52.57  6855.9   51.17
  7014.6   54.57  7506.4   54.77  7616.4   56.77  7626.4   57.57  7636.4   59.97
#Mann= 5 , 1 , 0
  2839.5      .1       0  4963.8     .04       0  5035.3     .99       0
  5409.9     .14       0  7014.6     .99       0
#XS Ineff= 2 , 0
       0  4965.3    53.5    5045       0    53.5
Permanent Ineff=
       F       F
Bank Sta=4963.8,5035.3
XS Rating Curve= 0 ,0
Exp/Cntr=0.5,0.3

Type RM Length L Ch R = 3 ,2430.0  ,,,
BEGIN DESCRIPTION:
FUQUA ROAD
Structure ID: C74-3
END DESCRIPTION:
Bridge Culvert--1,0,-1,-1, 0
Deck Dist Width WeirC Skew NumUp NumDn MinLoCord MaxHiCord MaxSubmerge Is_Ogee
10,94.2,2.6,0, 60, 60, , , 0.95, 0, 1,1,,
  2839.5  3579.5  3619.5  3649.5  3709.5  3729.5  3769.5  3789.5  3809.5    3968
    4038    4078    4198    4208    4488  4517.9  4546.1  4634.9  4820.4  4908.3
 4961.59  4961.7 4962.21  4962.3  4963.8 5036.79  5036.9  5037.2 5037.31  5049.2
  5117.2    5198  5236.4  5382.5  5411.1  5581.1  5605.8  5655.8  5685.8  5695.8
  5815.8  5825.8  5845.8  5867.6  5935.8  5965.8  6028.6  6119.4  6337.9  6546.6
  6606.6  6746.6  6855.9    6980    7010  7506.4  7586.4  7616.4  7626.4  7636.4
    57.9    56.5    55.9    56.2    55.2    54.3    55.3    55.1    54.3    56.1
    54.9    55.5    55.4    55.8    53.3    54.5   53.86   54.95   58.24   59.37
   59.61   63.11   63.11   63.11   63.11   62.91   62.91   62.91   59.41   59.32
    58.8   56.73   55.74   54.31    54.3   53.79   53.71   53.56   53.47   53.43
   53.06   53.03   52.97    52.9   52.94   52.96      53   53.06   53.07   53.46
   53.52   53.67   53.56    53.5   54.61    54.8    56.6    56.8    57.6      60
    57.9    56.5    55.9    56.2    55.2    54.3    55.3    55.1    54.3    56.1
    54.9    55.5    55.4    55.8    53.3    54.5   53.85   54.54   56.22   56.25
   54.34   54.34   54.32   56.01   56.01   55.81   53.03   52.88   52.82   46.69
   45.41   44.69      45   46.41    53.2    51.6      51    51.2    50.8    51.4
    51.3    50.7    50.4   50.66    51.2    50.8    50.9    52.3    51.7    51.8
    52.6    52.2    51.2    53.4    54.6    54.8    56.6    56.8    57.6      60
  2839.5  3579.5  3619.5  3649.5  3709.5  3729.5  3769.5  3789.5  3809.5    3968
    4038    4078    4198    4208    4488  4517.9  4546.1  4634.9  4820.4  4908.3
 4961.59  4961.7 4962.21  4962.3  4963.8 5036.79  5036.9  5037.2 5037.31  5049.2
  5117.2    5198  5236.4  5382.5  5411.1  5581.1  5605.8  5655.8  5685.8  5695.8
  5815.8  5825.8  5845.8  5867.6  5935.8  5965.8  6028.6  6119.4  6337.9  6546.6
  6606.6  6746.6  6855.9    6980    7010  7506.4  7586.4  7616.4  7626.4  7636.4
    57.9    56.5    55.9    56.2    55.2    54.3    55.3    55.1    54.3    56.1
    54.9    55.5    55.4    55.8    53.3    54.5   53.86   54.95   58.24   59.37
   59.61   63.11   63.11   63.11   63.11   62.91   62.91   62.91   59.41   59.32
    58.8   56.73   55.74   54.31    54.3   53.79   53.71   53.56   53.47   53.43
   53.06   53.03   52.97    52.9   52.94   52.96      53   53.06   53.07   53.46
   53.52   53.67   53.56    53.5   54.61    54.8    56.6    56.8    57.6      60
   57.82   56.42   55.82   56.12   55.12   54.22   55.22   55.02   54.22   56.02
   54.82   55.42   55.32   55.72   53.22   54.42   53.77   54.46   56.14   56.17
   54.26   54.26   54.24   55.93   55.93   55.73   52.95    52.8   52.74   46.61
   45.33   44.61   44.92   46.33   53.12   51.52   50.92   51.12   50.72   51.32
   51.22   50.62   50.32   50.58   51.12   50.72   50.82   52.22   51.62   51.72
   52.52   52.12   51.12   53.32   54.52   54.72   56.52   56.72   57.52   59.92
Pier Skew, UpSta & Num, DnSta & Num=  ,4980.4, 2 ,4980.4, 2 , 0 , 0 , 0 ,,
     1.2     1.2
   45.05   56.97
     1.2     1.2
   44.97   56.89
Pier Skew, UpSta & Num, DnSta & Num=  ,5020.1, 2 ,5020.1, 2 , 0 , 0 , 0 ,,
     1.2     1.2
   45.37   56.86
     1.2     1.2
   45.29   56.78
Abutment Skew #Up #Dn= , 2 , 2
  4962.1  4989.5
   56.01   42.06
  4962.1  4989.5
   55.93   41.98
Abutment Skew #Up #Dn= , 2 , 2
  5010.4 5036.99
   42.03   55.81
  5010.4 5036.99
   41.95   55.73
BR Coef= 1 , 1 , 0 ,1.25, 0 ,,,0.8,0,2,0,
WSPro=,,,, 1 ,,,, 0 ,,,, 0 ,,,,-1 ,-1 ,-1 , 0 , 0 , 0 , 0 , 0
BR U #Sta/Elev= 117
  2839.5    57.9  3339.5      57  3359.5    56.9  3579.5    56.5  3619.5    55.9
  3649.5    56.2  3709.5    55.2  3729.5    54.3  3769.5    55.3  3789.5    55.1
  3809.5    54.3    3968    56.1    4038    54.9    4078    55.5    4198    55.4
    4208    55.8    4308    54.8    4488    53.3  4517.9    54.5    4518    54.5
  4530.2    54.5  4543.2   53.97    4546   53.86  4546.1   53.85  4634.9   54.54
  4726.4   55.19  4820.4   56.22  4876.2   56.24  4908.3   56.25 4961.59   54.34
  4961.7   54.34 4961.81   54.33  4962.1   54.32 4962.21   54.32  4962.3   54.31
  4963.8   54.26  4980.4   46.33  4989.4   42.11  4989.5   42.06  4993.7   41.56
  5001.4   41.34  5001.8   41.33  5008.3   41.67  5010.3   42.03  5010.4   42.03
  5010.5   42.03  5020.1   46.66  5035.3   53.86 5036.79   53.09  5036.9   53.03
 5036.99   52.99  5037.1   52.93  5037.2   52.88 5037.31   52.82  5049.2   46.69
  5101.8   45.55  5117.2   45.41    5198   44.69  5236.4      45  5315.9   45.65
  5359.4   46.15  5382.5   46.41  5409.9   52.92  5411.1    53.2  5417.6   53.14
  5581.1    51.6  5605.8      51  5655.8    51.2  5685.8    50.8  5695.8    51.4
  5815.8    51.3  5825.8    50.7  5845.8    50.4  5867.6   50.66  5895.8      51
  5925.8    50.9  5935.8    51.2  5965.8    50.8  5968.6    50.8  5988.6      51
  6028.6    50.9  6119.4    52.3  6175.5   52.23  6225.5   52.16  6269.4    52.1
  6320.5    51.8  6337.9    51.7  6397.9   51.73  6546.6    51.8  6606.6    52.6
  6636.6    52.3  6746.6    52.2  6766.6    51.8  6770.8   51.77  6816.6    51.5
  6825.9    51.7  6855.9    51.2  6895.8   51.68  6905.9    51.8  6955.9    53.1
  6965.9      53    6980    53.4    6990    53.7    7010    54.6  7014.6    54.6
    7055    54.6  7135.8   54.57  7136.5   54.57  7201.5   54.54  7221.5   54.53
  7231.5   54.53  7296.4    54.5  7506.4    54.8  7586.4    56.6  7616.4    56.8
  7626.4    57.6  7636.4      60
BR U #Mann= 5
  2839.5      .1  4963.8     .04  5035.3     .99  5409.9     .14  7014.6     .99
BR U Banks=4963.8,5035.3
BR D #Sta/Elev= 117
  2839.5   57.82  3339.5   56.92  3359.5   56.82  3579.5   56.42  3619.5   55.82
  3649.5   56.12  3709.5   55.12  3729.5   54.22  3769.5   55.22  3789.5   55.02
  3809.5   54.22    3968   56.02    4038   54.82    4078   55.42    4198   55.32
    4208   55.72    4308   54.72    4488   53.22  4517.9   54.42    4518   54.42
  4530.2   54.42  4543.2   53.89    4546   53.78  4546.1   53.77  4634.9   54.46
  4726.4   55.11  4820.4   56.14  4876.2   56.16  4908.3   56.17 4961.59   54.26
  4961.7   54.26 4961.81   54.25  4962.1   54.24 4962.21   54.24  4962.3   54.23
  4963.8   54.18  4980.4   46.25  4989.4   42.03  4989.5   41.98  4993.7   41.48
  5001.4   41.26  5001.8   41.25  5008.3   41.59  5010.3   41.95  5010.4   41.95
  5010.5   41.95  5020.1   46.58  5035.3   53.78 5036.79   53.01  5036.9   52.95
 5036.99   52.91  5037.1   52.85  5037.2    52.8 5037.31   52.74  5049.2   46.61
  5101.8   45.47  5117.2   45.33    5198   44.61  5236.4   44.92  5315.9   45.57
  5359.4   46.07  5382.5   46.33  5409.9   52.84  5411.1   53.12  5417.6   53.06
  5581.1   51.52  5605.8   50.92  5655.8   51.12  5685.8   50.72  5695.8   51.32
  5815.8   51.22  5825.8   50.62  5845.8   50.32  5867.6   50.58  5895.8   50.92
  5925.8   50.82  5935.8   51.12  5965.8   50.72  5968.6   50.72  5988.6   50.92
  6028.6   50.82  6119.4   52.22  6175.5   52.15  6225.5   52.08  6269.4   52.02
  6320.5   51.72  6337.9   51.62  6397.9   51.65  6546.6   51.72  6606.6   52.52
  6636.6   52.22  6746.6   52.12  6766.6   51.72  6770.8   51.69  6816.6   51.42
  6825.9   51.62  6855.9   51.12  6895.8    51.6  6905.9   51.72  6955.9   53.02
  6965.9   52.92    6980   53.32    6990   53.62    7010   54.52  7014.6   54.52
    7055   54.52  7135.8   54.49  7136.5   54.49  7201.5   54.46  7221.5   54.45
  7231.5   54.45  7296.4   54.42  7506.4   54.72  7586.4   56.52  7616.4   56.72
  7626.4   57.52  7636.4   59.92
BR D #Mann= 5
  2839.5      .1  4963.8     .04  5035.3     .99  5409.9     .14  7014.6     .99
BR D Banks=4963.8,5035.3
BC Design=,, 0 ,, 0 ,,,,,,
BC HTab HWMax=59.97
BC Use User HTab Curves=0
BC User HTab FreeFlow(D)= 0

Type RM Length L Ch R = 1 ,2372.9  ,254.9,254.9,254.9
BEGIN DESCRIPTION:
Downstream Section of Bridge/Culvert/Weir
END DESCRIPTION:
XS GIS Cut Line= 6
       3090608.6     13787534.98      3091832.75     13787473.49
      3092545.23     13787225.76      3093939.61     13787282.44
      3094715.31     13787504.33      3095101.12     13787097.67
#Sta/Elev= 30
  2839.5   57.81  3579.5   56.41  3729.5   54.21    3968   56.01    4038   54.81
    4208   55.71    4488   53.21  4517.9   54.41  4546.1   53.76  4908.3   56.16
  4963.8   54.17  4989.5   41.97  5001.8   41.24  5010.5   41.94  5035.3   53.77
  5049.2    46.6    5198    44.6  5382.5   46.32  5409.9   52.83  5605.8   50.91
  5815.8   51.21  5845.8   50.31  6119.4   52.21  6606.6   52.51  6855.9   51.11
  7014.6   54.51  7506.4   54.71  7616.4   56.71  7626.4   57.51  7636.4   59.91
#Mann= 5 , 1 , 0
  2839.5      .1       0  4963.8     .04       0  5035.3     .99       0
  5409.9     .14       0  7014.6     .99       0
#XS Ineff= 2 , 0
       0  4965.3    53.5    5045       0    53.5
Permanent Ineff=
       F       F
Bank Sta=4963.8,5035.3
XS Rating Curve= 0 ,0
Exp/Cntr=0.5,0.3

Type RM Length L Ch R = 1 ,2118.0  ,298.4,365.1,419
BEGIN DESCRIPTION:
Cross Section 2118.0-Interpolated
END DESCRIPTION:
XS GIS Cut Line= 6
      3090349.66     13787567.74      3092615.98     13787491.73
      3093935.75     13787498.57      3094631.26     13787580.92
      3095081.97     13787323.09      3095190.16     13786856.16
#Sta/Elev= 30
    2648    58.7    2678    57.3    3478    56.1    3508    57.1  3934.6   55.57
  4942.8    54.3  4952.8    53.8  4957.3   51.64  4964.1    49.6  4989.6   45.21
  4990.7    41.2  4999.8   40.96  5009.1   41.17  5009.6   41.77  5010.6   45.19
  5033.3   53.04  5281.1    54.9  5341.1    56.7  5501.1    55.4  5781.1    55.4
  5831.1    54.1    6100   56.12  6111.1    56.3  6141.1      54    7214    53.3
    7244    54.6  7463.2    54.4  7843.2    56.4  7903.2      59  7934.4    59.1
#Mann= 6 , 1 , 0
    2648      .2       0    2648      .1       0  3934.6     .14       0
  4957.3     .04       0  5033.3     .14       0    6100     .99       0
Bank Sta=4957.3,5033.3
XS Rating Curve= 0 ,0
Exp/Cntr=0.3,0.1

Type RM Length L Ch R = 1 ,1752.9  ,79.3,93.9,93.1
BEGIN DESCRIPTION:
Cross Section 1752.9-Interpolated
END DESCRIPTION:
XS GIS Cut Line= 6
      3090285.11     13787674.79      3092809.88     13787817.34
      3092875.34     13787786.09      3094352.88     13787853.88
      3095101.79     13787597.26      3095196.66     13786887.96
#Sta/Elev= 30
  2430.3    58.7  3180.3    55.9  3380.3    56.6  3620.3      56  4322.1    55.8
  4392.1    54.1  4953.6    54.2  4957.3   51.23  4964.1   49.19  4989.6    44.8
  4990.4   41.43  4990.7   40.79  4999.8   40.55  5009.1   40.76  5009.6   41.36
  5010.6   44.78  5022.7   48.59  5033.3   52.63  5051.7    55.8  5809.8    55.8
  5939.8    54.2  5989.8    52.1    6000   52.14  6891.6    53.4  7343.2    53.1
  7373.2    52.7  7413.2    54.1  7793.2    55.5  7823.2    55.2  8018.9    58.5
#Mann= 4 , 1 , 0
  2430.3      .1       0  4957.3     .04       0  5033.3      .1       0
    6000     .99       0
Bank Sta=4957.3,5033.3
XS Rating Curve= 0 ,0
Exp/Cntr=0.5,0.3

Type RM Length L Ch R = 1 ,1659.0  ,56.6,56.6,56.6
BEGIN DESCRIPTION:
Upstream Section of Bridge/Culvert/Weir
END DESCRIPTION:
XS GIS Cut Line= 6
        3090297.     13787698.42      3092293.32     13787845.52
       3094477.8     13787953.46      3094851.36     13787845.58
      3095136.99     13787676.98       3095215.6     13787025.55
#Sta/Elev= 30
  2412.9   59.01  2432.9   57.81  3372.9   56.71  3652.9   55.41  3672.9   56.21
  4067.5   56.61  4383.9   54.31  4834.3   53.63  4952.4   52.52  4957.1   51.13
  4989.6    44.7  4990.7   40.69  4999.8   40.45  5009.1   40.66  5010.6   44.68
  5033.3   52.53  5042.4   53.65  5784.3   54.81  5924.3   54.41  5974.3   52.11
  6034.3   52.01  6074.3   53.41    6500   53.11  7082.1   54.21  7272.1   52.11
  7312.1   53.11  7421.4   52.51  7461.4   53.91  7901.4   56.11  7981.4   57.51
#Mann= 4 , 1 , 0
  2412.9      .1       0  4957.1     .04       0  5033.3      .1       0
    6500     .99       0
#XS Ineff= 2 , 0
       0    4953    53.4    5035       0    53.4
Permanent Ineff=
       F       F
Bank Sta=4957.1,5033.3
XS Rating Curve= 0 ,0
Exp/Cntr=0.5,0.3

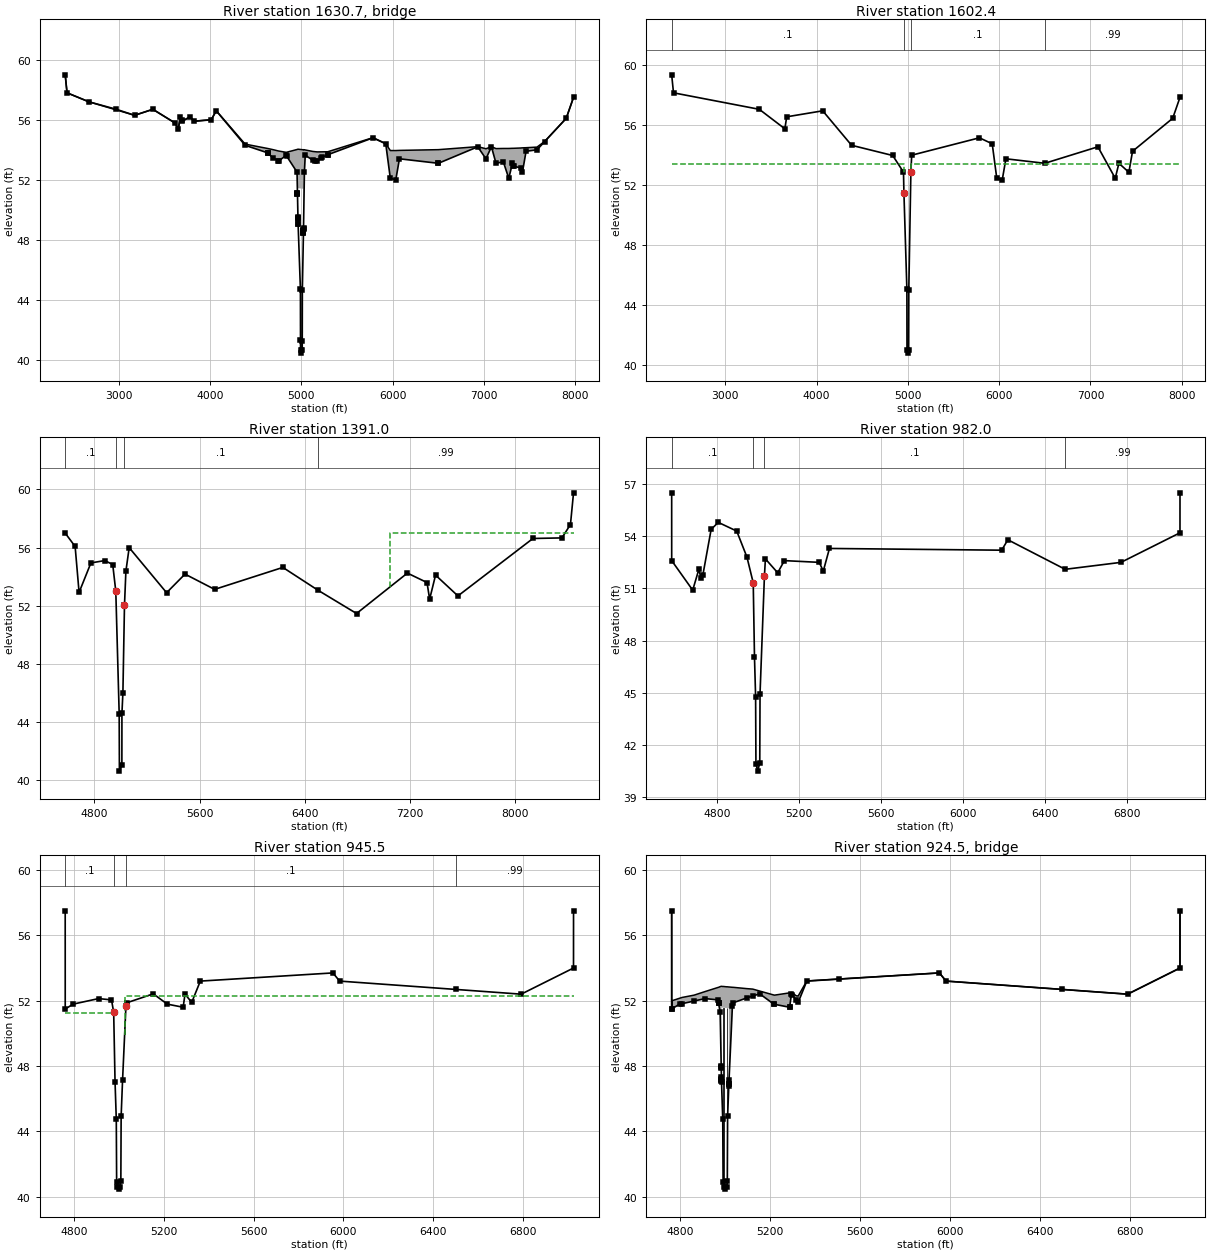
Type RM Length L Ch R = 3 ,1630.7  ,,,
BEGIN DESCRIPTION:
WEST FUQUA ROAD
Structure ID: C47-2
END DESCRIPTION:
Bridge Culvert--1,0,-1,-1, 0
Deck Dist Width WeirC Skew NumUp NumDn MinLoCord MaxHiCord MaxSubmerge Is_Ogee
10,36.6,2.6,0, 49, 49, , , 0.95, 0, 1,1,,
  2412.9  2432.9  2672.9  3172.9  3372.9  3612.9  3652.9  3672.9  3692.9  3782.9
  3822.9  4012.9  4067.5  4383.9  4629.1  4690.1  4749.9  4834.3  4952.4 4962.71
  4962.8 5023.19  5023.3  5033.3  5042.4  5125.4  5173.6  5289.1  5784.3  5924.3
  5974.3  6034.3  6074.3  6500.8  6932.1  7022.1  7082.1  7132.1  7212.1  7272.1
  7312.1  7321.4  7401.4  7421.4  7461.4  7581.4  7665.2  7901.4  7981.4
      59    57.8    57.2    56.3    56.7    55.8    55.4    56.2   55.91   56.21
   55.91   56.01   56.61   54.38   54.09   54.01   53.92   53.83   54.02   54.04
   54.04      54   54.01      54   53.99   53.89   53.86   53.87   54.81   54.41
   53.95   53.95   53.96   54.01   54.21   54.07   54.21   54.08   54.09   54.09
    54.1    54.1   54.12   54.13   54.14   54.18   54.56    56.1    57.5
      59    57.8    57.2    56.3    56.7    55.8    55.4    56.2    55.9    56.2
    55.9      56    56.6    54.3    53.8   53.46   53.26   53.62   52.51   49.46
   51.44    51.4   48.71   52.52   53.64    53.3   53.25   53.67    54.8    54.4
    52.1      52    53.4    53.1    54.2    53.4    54.2    53.1    53.2    52.1
    53.1    52.9    52.8    52.5    53.9      54   54.55    56.1    57.5
  2412.9  2432.9  2672.9  3172.9  3372.9  3612.9  3652.9  3672.9  3692.9  3782.9
  3822.9  4012.9  4067.5  4383.9  4629.1  4690.1  4749.9  4834.3  4952.4 4962.71
  4962.8 5023.19  5023.3  5033.3  5042.4  5125.4  5173.6  5289.1  5784.3  5924.3
  5974.3  6034.3  6074.3  6500.8  6932.1  7022.1  7082.1  7132.1  7212.1  7272.1
  7312.1  7321.4  7401.4  7421.4  7461.4  7581.4  7665.2  7901.4  7981.4
      59    57.8    57.2    56.3    56.7    55.8    55.4    56.2   55.91   56.21
   55.91   56.01   56.61   54.38   54.09   54.01   53.92   53.83   54.02   54.04
   54.04      54   54.01      54   53.99   53.89   53.86   53.87   54.81   54.41
   53.95   53.95   53.96   54.01   54.21   54.07   54.21   54.08   54.09   54.09
    54.1    54.1   54.12   54.13   54.14   54.18   54.56    56.1    57.5
   58.89   57.69   57.09   56.19   56.59   55.69   55.29   56.09   55.79   56.09
   55.79   55.89   56.49   54.19   53.69   53.35   53.15   53.51    52.4   49.35
   51.33   51.29    48.6   52.41   53.53   53.19   53.14   53.56   54.69   54.29
   51.99   51.89   53.29   52.99   54.09   53.29   54.09   52.99   53.09   51.99
   52.99   52.79   52.69   52.39   53.79   53.89   54.44   55.99   57.39
Abutment Skew #Up #Dn= , 2 , 2
  4962.6  4964.1
   51.44   49.06
  4962.6  4964.1
   51.33   48.95
BR Coef= 1 , 1 , 0 ,1.25, 0 ,,,0.8,0,2,0,
WSPro=,,,, 1 ,,,, 0 ,,,, 0 ,,,,-1 ,-1 ,-1 , 0 , 0 , 0 , 0 , 0
BR U #Sta/Elev= 82
  2412.9      59  2432.9    57.8  2672.9    57.2  2972.9    56.7  3172.9    56.3
  3372.9    56.7  3612.9    55.8  3652.9    55.4  3672.9    56.2  3687.1   55.99
  3692.9    55.9  3782.9    56.2  3822.9    55.9  4012.9      56  4067.5    56.6
  4383.9    54.3  4629.1    53.8  4629.2   53.79  4630.4   53.78  4690.1   53.46
  4744.8   53.28  4749.9   53.26  4834.3   53.62  4837.2   53.59  4952.4   52.51
  4957.1   51.12 4957.19   51.09  4957.3   51.06 4957.41   51.03  4962.6   49.49
 4962.71   49.46  4962.8   49.43    4963   49.38    4964   49.08  4964.1   49.06
  4989.6   44.69  4990.4   41.32  4990.7   40.68  4999.8   40.44  5009.1   40.65
  5009.6   41.25  5010.6   44.67  5022.6   48.45  5022.7   48.48 5022.86   48.54
 5022.97   48.58 5023.08   48.62 5023.19   48.67  5023.3   48.71  5023.5   48.78
  5033.3   52.52  5042.4   53.64  5125.4    53.3  5145.1   53.28  5173.6   53.25
  5219.9   53.46  5230.1   53.49  5288.2   53.67  5289.1   53.67  5784.3    54.8
  5924.3    54.4  5974.3    52.1  6034.3      52  6074.3    53.4    6500    53.1
  6500.8    53.1  6932.1    54.2  7022.1    53.4  7082.1    54.2  7132.1    53.1
  7212.1    53.2  7272.1    52.1  7312.1    53.1  7321.4    52.9  7325.2    52.9
  7401.4    52.8  7421.4    52.5  7461.4    53.9  7581.4      54  7665.2   54.55
  7901.4    56.1  7981.4    57.5
BR U #Mann= 4
  2412.9      .1  4957.1    .015  5033.3      .1    6500     .99
BR U Banks=4957.1,5033.3
BR D #Sta/Elev= 82
  2412.9   58.89  2432.9   57.69  2672.9   57.09  2972.9   56.59  3172.9   56.19
  3372.9   56.59  3612.9   55.69  3652.9   55.29  3672.9   56.09  3687.1   55.88
  3692.9   55.79  3782.9   56.09  3822.9   55.79  4012.9   55.89  4067.5   56.49
  4383.9   54.19  4629.1   53.69  4629.2   53.68  4630.4   53.67  4690.1   53.35
  4744.8   53.17  4749.9   53.15  4834.3   53.51  4837.2   53.48  4952.4    52.4
  4957.1   51.01 4957.19   50.98  4957.3   50.95 4957.41   50.92  4962.6   49.38
 4962.71   49.35  4962.8   49.32    4963   49.27    4964   48.97  4964.1   48.95
  4989.6   44.58  4990.4   41.21  4990.7   40.57  4999.8   40.33  5009.1   40.54
  5009.6   41.14  5010.6   44.56  5022.6   48.34  5022.7   48.37 5022.86   48.43
 5022.97   48.47 5023.08   48.51 5023.19   48.56  5023.3    48.6  5023.5   48.67
  5033.3   52.41  5042.4   53.53  5125.4   53.19  5145.1   53.17  5173.6   53.14
  5219.9   53.35  5230.1   53.38  5288.2   53.56  5289.1   53.56  5784.3   54.69
  5924.3   54.29  5974.3   51.99  6034.3   51.89  6074.3   53.29    6500   52.99
  6500.8   52.99  6932.1   54.09  7022.1   53.29  7082.1   54.09  7132.1   52.99
  7212.1   53.09  7272.1   51.99  7312.1   52.99  7321.4   52.79  7325.2   52.79
  7401.4   52.69  7421.4   52.39  7461.4   53.79  7581.4   53.89  7665.2   54.44
  7901.4   55.99  7981.4   57.39
BR D #Mann= 4
  2412.9      .1  4957.1    .015  5033.3      .1    6500     .99
BR D Banks=4957.1,5033.3
BC Design=,, 0 ,, 0 ,,,,,,
BC HTab HWMax=59.01
BC Use User HTab Curves=0
BC User HTab FreeFlow(D)= 0

Type RM Length L Ch R = 1 ,1602.4  ,211.4,211.4,211.4
BEGIN DESCRIPTION:
Downstream Section of Bridge/Culvert/Weir
END DESCRIPTION:
XS GIS Cut Line= 6
      3090304.55     13787754.52      3092300.88     13787901.62
      3094485.36     13788009.56      3094858.92     13787901.68
      3095144.55     13787733.08      3095223.15     13787081.64
#Sta/Elev= 30
  2412.9   59.32  2432.9   58.12  3372.9   57.02  3652.9   55.72  3672.9   56.52
  4067.5   56.92  4383.9   54.62  4834.3   53.94  4952.4   52.83  4957.1   51.44
  4989.6   45.01  4990.7      41  4999.8   40.76  5009.1   40.97  5010.6   44.99
  5033.3   52.84  5042.4   53.96  5784.3   55.12  5924.3   54.72  5974.3   52.42
  6034.3   52.32  6074.3   53.72    6500   53.42  7082.1   54.52  7272.1   52.42
  7312.1   53.42  7421.4   52.82  7461.4   54.22  7901.4   56.42  7981.4   57.82
#Mann= 4 , 1 , 0
  2412.9      .1       0  4957.1     .04       0  5033.3      .1       0
    6500     .99       0
#XS Ineff= 2 , 0
       0    4953    53.4    5035       0    53.4
Permanent Ineff=
       F       F
Bank Sta=4957.1,5033.3
XS Rating Curve= 0 ,0
Exp/Cntr=0.5,0.3

Type RM Length L Ch R = 1 ,1391.0  ,515.8,409,148.1
BEGIN DESCRIPTION:
Cross Section 1391.0-Interpolated
END DESCRIPTION:
XS GIS Cut Line= 6
      3092565.25     13788198.14      3093097.83     13788073.36
       3094194.9     13788129.42      3094870.03     13788069.62
      3095137.38     13787776.88      3095343.44     13786667.53
#Sta/Elev= 30
  4579.1      57  4654.5   56.08  4684.5   52.92  4774.5   54.95  4879.5   55.11
  4940.2   54.84 4963.49      53 4989.19   44.59 4990.89   40.63 5009.69   41.03
 5010.09    44.6 5017.49   46.02 5029.49   52.03  5040.2   54.38  5065.2      56
  5349.4    52.9  5489.4   54.18  5714.4   53.13  6232.9   54.64    6500   53.07
  6792.9   51.47  7179.2   54.25  7328.2    53.6  7348.2   52.46  7393.2   54.11
  7563.2   52.68  8133.2   56.63  8353.2   56.67  8418.2   57.59  8441.6   59.77
#Mann= 4 , 1 , 0
  4579.1      .1       0 4963.49     .04       0 5029.49      .1       0
    6500     .99       0
#XS Ineff= 2 , 0
       0                    7050       0      57
Permanent Ineff=
       F       F
Bank Sta=4963.49,5029.49
XS Rating Curve= 0 ,0
Exp/Cntr=0.3,0.1

Type RM Length L Ch R = 1 ,982.0   ,100.4,36.5,36.4
BEGIN DESCRIPTION:
Cross Section 982.0-Interpolated
END DESCRIPTION:
XS GIS Cut Line= 6
       3092761.5     13788542.56      3092987.09     13788571.95
      3093282.83     13788443.01      3093495.69     13788330.48
        3094876.     13788083.92      3095092.08      13787893.3
#Sta/Elev= 30
  4579.3    56.5  4579.4    52.6    4682    50.9    4712    52.1    4722    51.6
    4732    51.8    4772    54.4  4806.8    54.8  4896.8    54.3  4946.8    52.8
  4977.4   51.32  4983.5   47.05    4989   44.78  4990.6   40.92  4999.3   40.49
  5009.3   40.97  5010.6   44.95    5032    51.7  5036.8    52.7  5096.8    51.9
  5129.4    52.6  5299.4    52.5  5319.4      52  5349.4    53.3  6190.2    53.2
  6220.2    53.8    6500    52.1  6772.4    52.5  7060.4    54.2  7060.5    56.5
#Mann= 4 , 1 , 0
  4579.3      .1       0  4977.4     .04       0    5032      .1       0
    6500     .99       0
Bank Sta=4977.4,5032
XS Rating Curve= 0 ,0
Exp/Cntr=0.5,0.3

Type RM Length L Ch R = 1 ,945.5   ,42,42,42
BEGIN DESCRIPTION:
Upstream Section of Bridge/Culvert/Weir
END DESCRIPTION:
XS GIS Cut Line= 5
      3092961.56      13788617.3      3093007.07     13788606.91
      3093466.48     13788391.41      3094921.94     13788111.26
      3095068.64     13787939.48
#Sta/Elev= 29
  4761.7    57.5  4761.8   51.49  4796.8   51.79  4910.3   52.13  4967.7   52.05
  4977.4    51.3  4983.5   47.03    4989   44.76  4990.6    40.9  4992.7   40.62
  4999.3   40.47  5006.6   40.63  5009.3   40.95  5010.6   44.93  5016.9   47.13
    5032   51.68  5035.1   51.87  5153.7   52.42    5216   51.79  5286.6    51.6
  5294.8    52.4  5324.8    51.9    5363    53.2    5953    53.7    5983    53.2
    6500   52.69  6790.8    52.4  7023.8      54  7023.9    57.5
#Mann= 4 , 1 , 0
  4761.7      .1       0  4977.4     .04       0    5032      .1       0
    6500     .99       0
#XS Ineff= 2 , 0
       0  4977.6   51.25    5026       0    52.3
Permanent Ineff=
       F       F
Bank Sta=4977.4,5032
XS Rating Curve= 0 ,0
Exp/Cntr=0.5,0.3

Type RM Length L Ch R = 3 ,924.5   ,,,
BEGIN DESCRIPTION:
TIFFANY DRIVE
Structure ID: C47-1
END DESCRIPTION:
Bridge Culvert--1,0,-1,-1, 0
Deck Dist Width WeirC Skew NumUp NumDn MinLoCord MaxHiCord MaxSubmerge Is_Ogee
10,22,2.6,0, 52, 52, , , 0.95, 0, 1,1,,
  4761.7  4761.8  4763.6  4796.8  4808.3  4861.4  4910.3  4967.7 4970.39  4970.5
 4970.61  4977.4 4982.09  4982.2 4982.31  4983.1 4983.21  4983.3  4983.4  4983.5
    4989  4990.6  4992.7  4999.3  5006.6  5009.3  5010.6  5015.9 5016.19  5016.3
  5016.9    5032  5035.1  5095.6  5122.7  5153.7    5216    5219  5286.5  5286.6
  5294.8  5296.6  5315.8  5324.8    5363  5505.8    5953    5983    6500  6790.8
  7023.8  7023.9
    57.5   51.49      52   52.15    52.2   52.34   52.56   52.81   52.82   52.82
   52.82   52.86   52.88   52.88   52.88   52.88   52.88   52.88   52.88   52.88
   52.87   52.87   52.87   52.86   52.85   52.85   52.85   52.84   52.84   52.84
   52.84   52.82   52.82   52.74   52.71   52.59   52.35   52.34   52.48   52.48
    52.5    52.5    52.3   52.29   53.21   53.33    53.7    53.2   52.69    52.4
      54    57.5
    57.5   51.49   51.51   51.79   51.82   51.98   52.13   52.05   51.84   51.83
   51.83    51.3   48.02   47.94   47.86   47.31   47.23   47.17   51.58   51.58
   51.57   51.57   51.57   51.56   51.55   51.55   51.55   51.54   51.54   46.92
   47.13   51.68   51.87   52.17   52.29   52.42   51.79   51.78    51.6    51.6
    52.4   52.37   52.05    51.9    53.2   53.32    53.7    53.2   52.69    52.4
      54    57.5
  4761.7  4761.8  4763.6  4796.8  4808.3  4861.4  4910.3  4967.7 4970.39  4970.5
 4970.61  4977.4 4982.09  4982.2 4982.31  4983.1 4983.21  4983.3  4983.4  4983.5
    4989  4990.6  4992.7  4999.3  5006.6  5009.3  5010.6  5015.9 5016.19  5016.3
  5016.9    5032  5035.1  5095.6  5122.7  5153.7    5216    5219  5286.5  5286.6
  5294.8  5296.6  5315.8  5324.8    5363  5505.8    5953    5983    6500  6790.8
  7023.8  7023.9
    57.5   51.49      52   52.15    52.2   52.34   52.56   52.81   52.82   52.82
   52.82   52.86   52.88   52.88   52.88   52.88   52.88   52.88   52.88   52.88
   52.87   52.87   52.87   52.86   52.85   52.85   52.85   52.84   52.84   52.84
   52.84   52.82   52.82   52.74   52.71   52.59   52.35   52.34   52.48   52.48
    52.5    52.5    52.3   52.29   53.21   53.33    53.7    53.2   52.69    52.4
      54    57.5
   57.33   51.32   51.34   51.62   51.65   51.81   51.96   51.88   51.67   51.66
   51.66   51.13   47.85   47.77   47.69   47.14   47.06      47   51.41   51.41
    51.4    51.4    51.4   51.39   51.38   51.38   51.38   51.37   51.37   46.75
   46.96   51.51    51.7      52   52.12   52.25   51.62   51.61   51.43   51.43
   52.23    52.2   51.88   51.73   53.03   53.15   53.53   53.03   52.52   52.23
   53.83   57.33
Pier Skew, UpSta & Num, DnSta & Num=  ,4992.7, 2 ,4992.7, 2 , 0 , 0 , 0 ,,
       1       1
   39.61   52.57
       1       1
   39.44    52.4
Pier Skew, UpSta & Num, DnSta & Num=  ,5006.6, 2 ,5006.6, 2 , 0 , 0 , 0 ,,
       1       1
   39.62   52.55
       1       1
   39.45   52.38
BR Coef= 1 , 1 , 0 ,1.25, 0 ,,,0.8,0,2,0,
WSPro=,,,, 1 ,,,, 0 ,,,, 0 ,,,,-1 ,-1 ,-1 , 0 , 0 , 0 , 0 , 0
BR U #Sta/Elev= 52
  4761.7    57.5  4761.8   51.49  4763.6   51.51  4796.8   51.79  4808.3   51.82
  4861.4   51.98  4910.3   52.13  4967.7   52.05 4970.39   51.84  4970.5   51.83
 4970.61   51.83  4977.4    51.3 4982.09   48.02  4982.2   47.94 4982.31   47.86
  4983.1   47.31 4983.21   47.23  4983.3   47.17  4983.4    47.1  4983.5   47.03
    4989   44.76  4990.6    40.9  4992.7   40.62  4999.3   40.47  5006.6   40.63
  5009.3   40.95  5010.6   44.93  5015.9   46.78 5016.19   46.88  5016.3   46.92
  5016.9   47.13    5032   51.68  5035.1   51.87  5095.6   52.17  5122.7   52.29
  5153.7   52.42    5216   51.79    5219   51.78  5286.5    51.6  5286.6    51.6
  5294.8    52.4  5296.6   52.37  5315.8   52.05  5324.8    51.9    5363    53.2
  5505.8   53.32    5953    53.7    5983    53.2    6500   52.69  6790.8    52.4
  7023.8      54  7023.9    57.5
BR U #Mann= 4
  4761.7      .1  4977.4     .04    5032      .1    6500     .99
BR U Banks=4977.4,5032
BR D #Sta/Elev= 52
  4761.7   57.33  4761.8   51.32  4763.6   51.34  4796.8   51.62  4808.3   51.65
  4861.4   51.81  4910.3   51.96  4967.7   51.88 4970.39   51.67  4970.5   51.66
 4970.61   51.66  4977.4   51.13 4982.09   47.85  4982.2   47.77 4982.31   47.69
  4983.1   47.14 4983.21   47.06  4983.3      47  4983.4   46.93  4983.5   46.86
    4989   44.59  4990.6   40.73  4992.7   40.45  4999.3    40.3  5006.6   40.46
  5009.3   40.78  5010.6   44.76  5015.9   46.61 5016.19   46.71  5016.3   46.75
  5016.9   46.96    5032   51.51  5035.1    51.7  5095.6      52  5122.7   52.12
  5153.7   52.25    5216   51.62    5219   51.61  5286.5   51.43  5286.6   51.43
  5294.8   52.23  5296.6    52.2  5315.8   51.88  5324.8   51.73    5363   53.03
  5505.8   53.15    5953   53.53    5983   53.03    6500   52.52  6790.8   52.23
  7023.8   53.83  7023.9   57.33
BR D #Mann= 4
  4761.7      .1  4977.4     .04    5032      .1    6500     .99
BR D Banks=4977.4,5032
BC Design=,, 0 ,, 0 ,,,,,,
BC HTab HWMax=57.5
BC Use User HTab Curves=0
BC User HTab FreeFlow(D)= 0

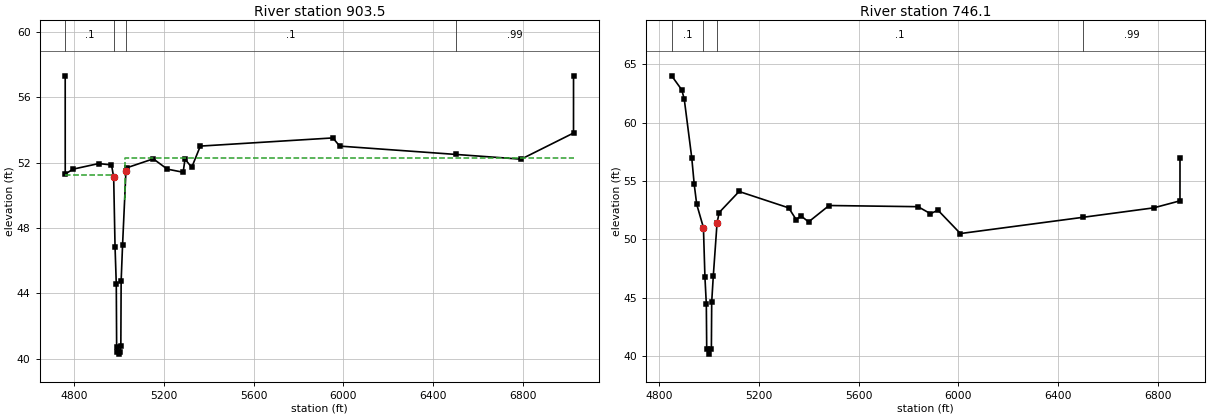
Type RM Length L Ch R = 1 ,903.5   ,157.4,157.4,157.4
BEGIN DESCRIPTION:
Downstream Section of Bridge/Culvert/Weir
END DESCRIPTION:
XS GIS Cut Line= 5
      3092981.26      13788654.4      3093026.77     13788644.01
      3093486.18     13788428.51      3094941.64     13788148.36
      3095088.34     13787976.57
#Sta/Elev= 29
  4761.7   57.32  4761.8   51.31  4796.8   51.61  4910.3   51.95  4967.7   51.87
  4977.4   51.12  4983.5   46.85    4989   44.58  4990.6   40.72  4992.7   40.44
  4999.3   40.29  5006.6   40.45  5009.3   40.77  5010.6   44.75  5016.9   46.95
    5032    51.5  5035.1   51.69  5153.7   52.24    5216   51.61  5286.6   51.42
  5294.8   52.22  5324.8   51.72    5363   53.02    5953   53.52    5983   53.02
    6500   52.51  6790.8   52.22  7023.8   53.82  7023.9   57.32
#Mann= 4 , 1 , 0
  4761.7      .1       0  4977.4     .04       0    5032      .1       0
    6500     .99       0
#XS Ineff= 2 , 0
       0  4977.6   51.25    5026       0    52.3
Permanent Ineff=
       F       F
Bank Sta=4977.4,5032
XS Rating Curve= 0 ,0
Exp/Cntr=0.5,0.3

Type RM Length L Ch R = 1 ,746.1   ,0,0,0
BEGIN DESCRIPTION:
Cross Section 746.1-Interpolated
END DESCRIPTION:
XS GIS Cut Line= 6
      3093167.61      13788705.9      3093205.04     13788721.32
        3093467.     13788599.47      3093752.98     13788501.82
      3094108.72     13788473.92      3095094.14     13788110.58
#Sta/Elev= 30
    4850      64  4890.5    62.8  4900.5      62  4930.5      57  4940.5    54.7
  4950.5      53  4977.4   51.01  4983.5   46.74    4989   44.47  4990.6   40.61
  4999.3   40.18  5009.3   40.66  5010.6   44.64  5016.9   46.84    5032   51.39
  5040.5    52.3  5120.5    54.1  5319.4    52.7  5349.4    51.7  5369.4      52
  5399.4    51.5  5481.6    52.9  5838.4    52.8  5888.4    52.2  5918.4    52.5
  6008.4    50.5    6500   51.89    6784    52.7  6889.4    53.3  6889.5      57
#Mann= 4 , 1 , 0
    4850      .1       0  4977.4     .04       0    5032      .1       0
    6500     .99       0
Bank Sta=4977.4,5032
XS Rating Curve= 0 ,0
Exp/Cntr=0.3,0.1
Stream Node=C147-00-00      ,C147-00-00_0007 , 0 , 0 ,Upstream end
Stream Node=C147-00-00      ,C147-00-00_0007 , 0 , 1 ,Downstream end

Chan Stop Cuts=-1
Use User Specified Reach Order=0
Composite Channel Slope=5